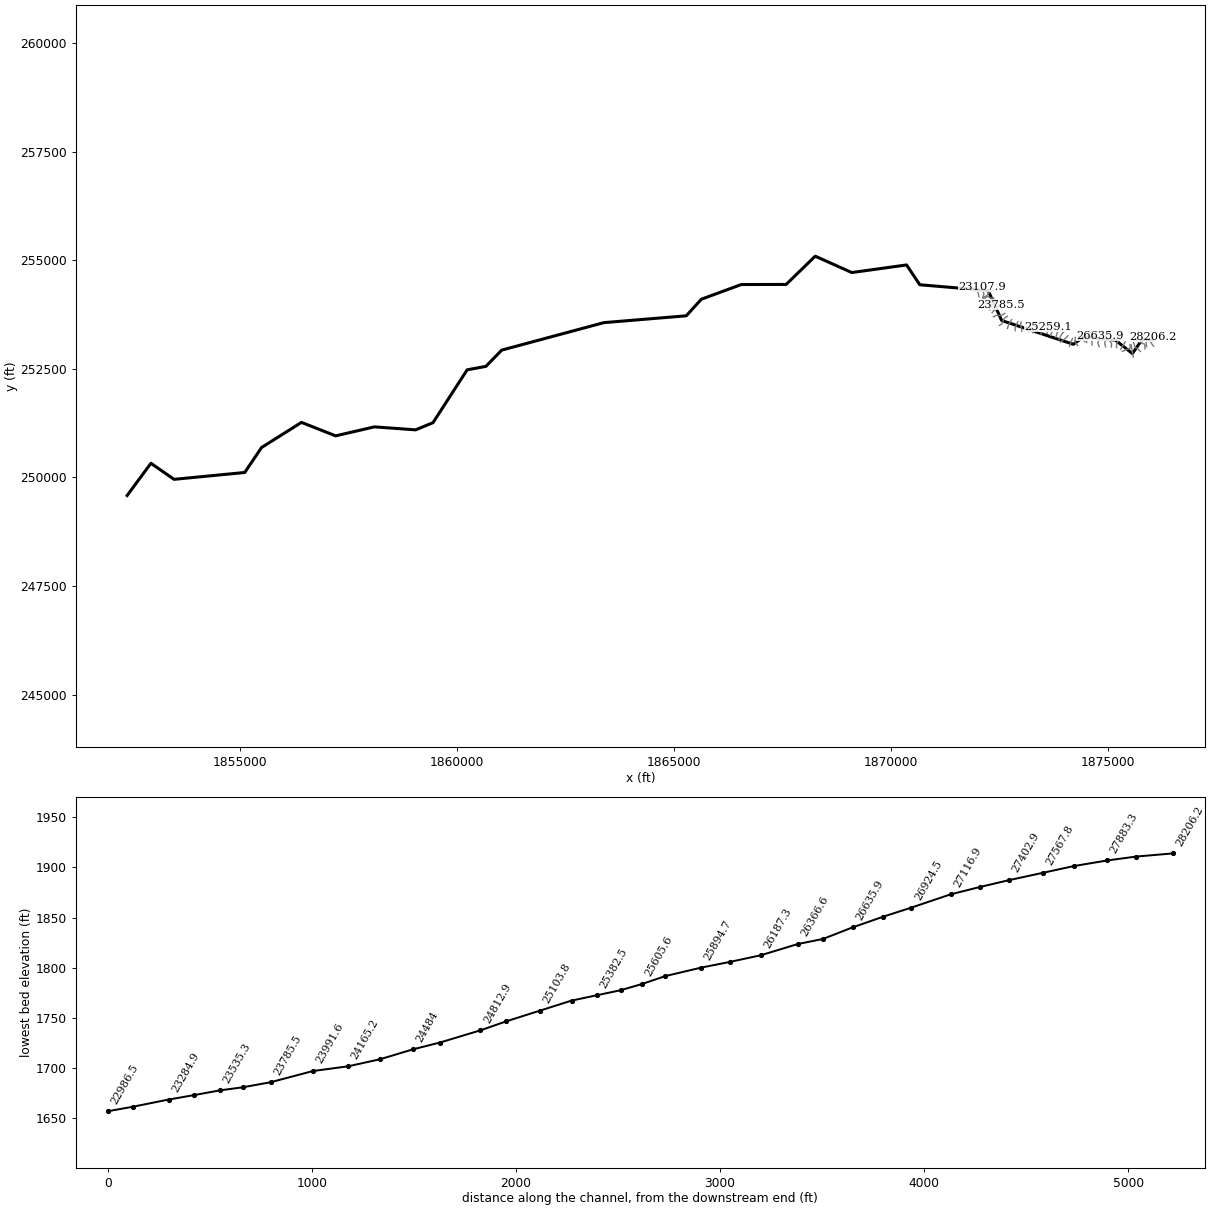
--- BUSHYFK.prj (project) ---

Proj Title=BUSHYFK
Current Plan=p01
Default Exp/Contr=0,0
English Units
Geom File=g01
Flow File=f01
Plan File=p01
BEGIN DESCRIPTION:
END DESCRIPTION:
DSS Export Rating Curves= 0
DSS Export Rating Curve Sorted= 0
DSS Export Volume Flow Curves= 0
DXF OffsetX= 0
DXF OffsetY= 0
DXF ScaleX= 0
DXF ScaleY= 0

--- BUSHYFK.p01 (plan) ---

Plan Title=Floodplain
Program Version=4.00
Geom File=g01
Flow File=f01
K Sum by GR=0
Std Step Tol=0.01
Critical Tol=0.01
Num of Std Step Trials=20
Max Error Tol=0.3
Flow Tol Ratio=0.001
Split Flow NTrial=30
Split Flow Tol=0.02
Split Flow Ratio=0.02
Log Output Level=0
Friction Slope Method=1
Unsteady Friction Slope Method=2
Unsteady Bridges Friction Slope Method=1
Global Log Level=0
CheckData=False
Run HTab=0
Run UNet=0
Run PostProcess=0
UNET Theta=0
UNET Theta Warmup=0
UNET ZTol=0
UNET ZSATol=0
UNET MxIter=0
UNET MaxInSteps=0
UNET DtIC=0
UNET DtMin=0
UNET MaxCRTS=0
UNET WFStab=0
UNET SFStab=0
UNET WFX=0
UNET SFX=0
UNET DSS MLevel=0
UNET DZMax Abort=0
UNET Convert EG Bridges=0
UNET Use Existing IB Tables=0
UNET Froude Limit=0
UNET Froude Power=0
Write IC File=0
Echo Input=False
Echo Output=False
Write Detailed=0

--- BUSHYFK.f01 (steady flow) ---

Flow Title=NFF Regression Equation
Program Version=4.00
Number of Profiles=1
Profile Names=P100yr
River Rch & RM=BUSHYFK,Main      ,28206.2
1188.344
River Rch & RM=BUSHYFK,Main      ,22986.5
1317.225
River Rch & RM=BUSHYFK,Main      ,22780.2
1516.545
River Rch & RM=BUSHYFK,Main      ,19161.4
1604.400
River Rch & RM=BUSHYFK,Main      ,15086.3
1747.911
River Rch & RM=BUSHYFK,Main      ,10372.4
1926.441
River Rch & RM=BUSHYFK,Main      ,7647.3
2137.149
River Rch & RM=BUSHYFK,Main      ,517.6
2368.616
River Rch & RM=BUSHYFK,Main      ,269.5
2369.691
Boundary for River Rch & Prof#=BUSHYFK,Main      ,1
Up Type=0
Dn Type=3
Dn Slope=0.010322

--- BUSHYFK.g01 (geometry) ---

Geom Title=USGS 10m DEM
Program Version=4.10

River Reach=BUSHYFK         ,Main
Reach XY= 30
     1876018.959      253169.466     1875782.792      253179.529
     1875557.153      252855.261     1875166.508       253163.54
     1874435.768      253239.784     1874196.589      253067.981
     1872545.409      253615.345     1872232.885      254305.358
     1870657.782      254439.063     1870352.698      254895.262
     1869090.651      254719.931     1868248.552      255097.187
     1867577.521      254446.345     1866543.235      254444.028
     1865624.958      254105.956     1865275.706      253723.816
     1863377.054      253566.459     1861023.404      252933.551
     1860658.783       252559.12     1860226.898      252479.899
     1859440.064      251262.629     1859040.075      251097.154
     1858089.392      251165.953     1857196.139      250958.879
     1856409.168      251269.164     1855488.571      250689.794
     1855101.699      250115.375     1853472.261       249957.53
      1852939.78      250327.535     1852390.962      249584.423

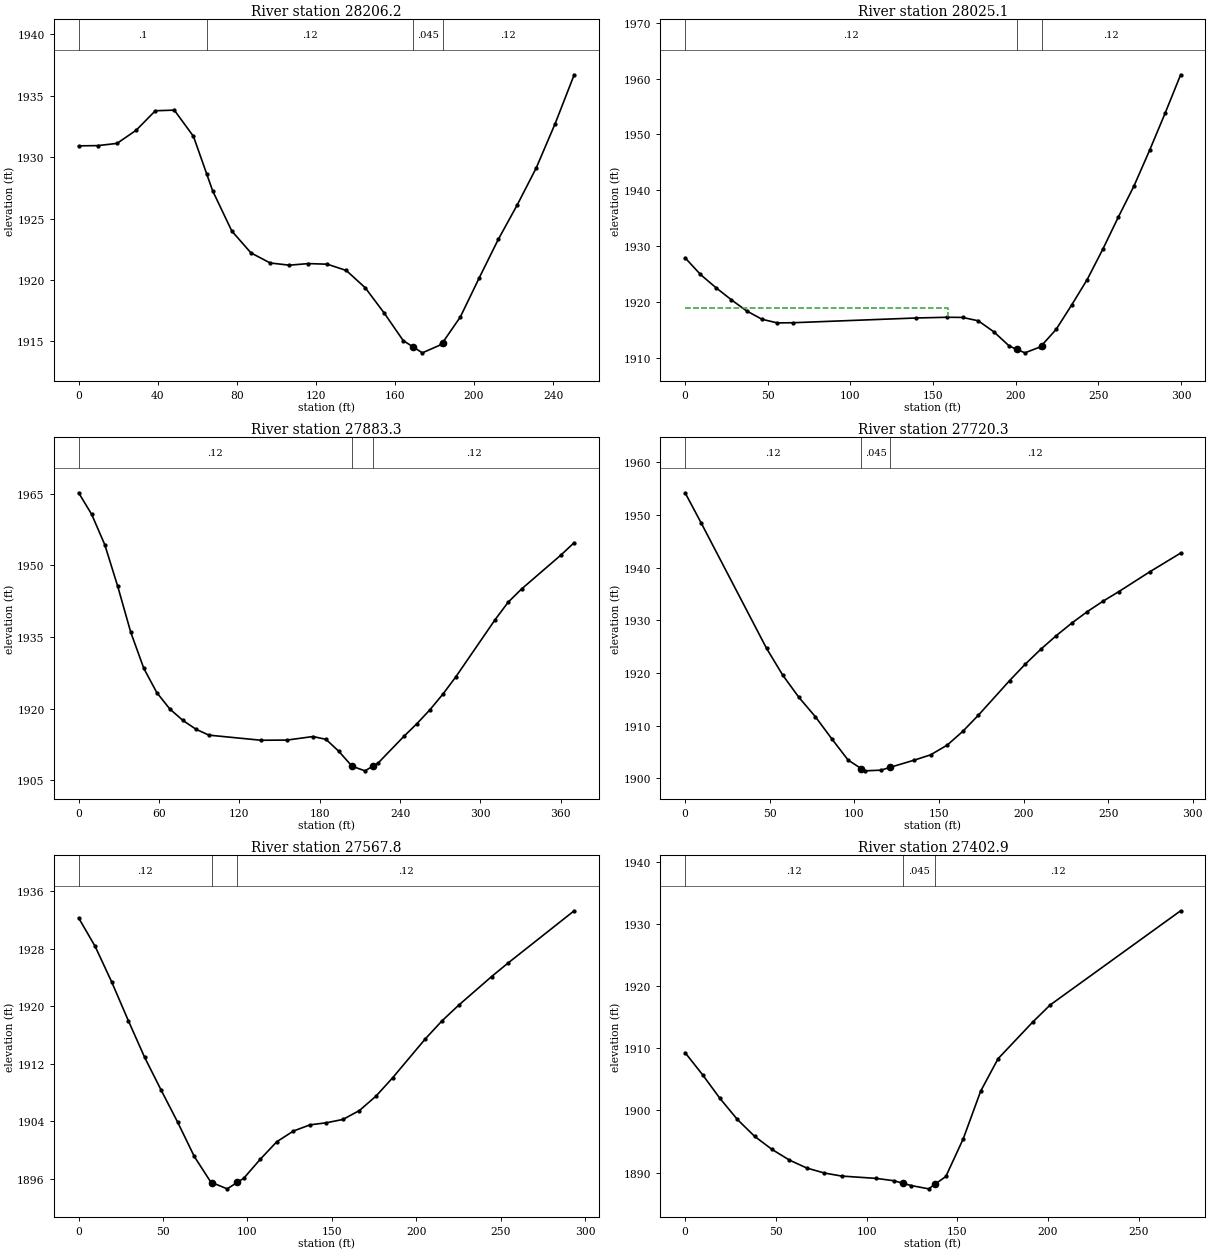
Type RM Length L Ch R = 1 ,28206.2 ,162.5,181.1,199.7
XS GIS Cut Line= 3
     1876045.535         253021.     1875983.686      253107.805
     1876032.514      253243.439
#Sta/Elev= 30
       0 1930.92     9.7 1930.94    19.4 1931.12    29.1 1932.19    38.8 1933.78
    48.4 1933.83    58.1 1931.69   64.781928.639    67.8 1927.26    77.5 1923.98
    87.2  1922.2    96.9 1921.38   106.6  1921.2   116.2 1921.33   125.8 1921.28
   135.4 1920.77     145 1919.36   154.6  1917.3   164.2 1915.06   169.1 1914.55
   173.9 1914.06   183.5 1914.74   184.1 1914.88   193.1 1916.98   202.7 1920.18
   212.3  1923.3   221.9 1926.11   231.5 1929.12   241.1 1932.74   250.7 1936.71
#Mann= 4 ,-1 , 0
       0      .1       0   64.78     .12       0   169.1    .045       0
   184.1     .12       0
Bank Sta=169.1,184.1
XS Rating Curve= 0 ,0
Exp/Cntr=0.3,0.1

Type RM Length L Ch R = 1 ,28025.1 ,125.8,141.8,157.7
XS GIS Cut Line= 3
     1875886.285      253013.564     1875865.452      253151.584
     1875793.837      253294.814
#Sta/Elev= 27
       0 1927.92     9.3 1924.93    18.6 1922.58    27.9 1920.42    37.2 1918.41
    46.5 1916.91    55.8 1916.26    65.1 1916.29   139.6 1917.14   158.4 1917.27
   167.8 1917.24   177.3 1916.64   186.7 1914.67   196.1 1912.11   200.6 1911.53
   205.5  1910.9   214.9 1911.97   215.6  1912.2   224.4  1915.1   233.8 1919.47
   243.2 1924.03   252.6 1929.44     262  1935.2   271.5 1940.79   280.9 1947.15
   290.3  1953.8   299.7 1960.69
#Mann= 3 ,-1 , 0
       0     .12       0   200.6    .045       0   215.6     .12       0
#XS Ineff= 2 , 0
          158.82 1918.92
Permanent Ineff=
       F       F
Bank Sta=200.6,215.6
XS Rating Curve= 0 ,0
Exp/Cntr=0.3,0.1

Type RM Length L Ch R = 1 ,27883.3 ,166,163,160
XS GIS Cut Line= 4
     1875848.525       252961.48     1875840.712      253068.251
     1875671.441      253141.168     1875636.285       253211.48
#Sta/Elev= 30
       0 1965.18     9.7 1960.68    19.5 1954.33    29.2 1945.59    38.9    1936
    48.7 1928.41    58.4 1923.35    68.1 1919.93    77.9 1917.53    87.6  1915.7
    97.3 1914.46   136.2 1913.39   155.6 1913.43     175 1914.17   184.7 1913.58
   194.4 1911.04   204.1 1907.96   213.8 1906.99  220.071908.023   223.5 1908.59
   242.9 1914.22   252.6 1916.87   262.3 1919.77     272 1923.05   281.7 1926.69
     311 1938.64   320.8 1942.31   330.7 1945.04   360.2 1952.17     370 1954.74
#Mann= 3 ,-1 , 0
       0     .12       0   204.1    .045       0  220.07     .12       0
Bank Sta=204.1,220.07
XS Rating Curve= 0 ,0
Exp/Cntr=0.3,0.1

Type RM Length L Ch R = 1 ,27720.3 ,172.4,152.5,132.5
XS GIS Cut Line= 4
     1875743.056      252901.584     1875680.556       252961.48
     1875621.962      252996.636     1875576.389      253126.845
#Sta/Elev= 27
       0 1954.18     9.6 1948.39    48.1 1924.68    57.7 1919.57    67.3 1915.34
      77 1911.68    86.6 1907.53    96.3 1903.47  104.031901.854   106.1 1901.42
   115.8 1901.55  121.121902.087   135.4 1903.45   145.1 1904.46   154.9 1906.31
   164.1 1908.92   173.3 1911.98   191.7 1918.53   200.9 1921.63   210.1 1924.47
   219.3 1927.07   228.5 1929.46   237.7 1931.64   246.9  1933.6   256.1 1935.39
   274.5 1939.17   292.8 1942.74
#Mann= 3 ,-1 , 0
       0     .12       0  104.03    .045       0  121.12     .12       0
Bank Sta=104.03,121.12
XS Rating Curve= 0 ,0
Exp/Cntr=0.3,0.1

Type RM Length L Ch R = 1 ,27567.8 ,195,164.9,134.5
XS GIS Cut Line= 2
     1875577.691       252773.98      1875526.91      253063.043
#Sta/Elev= 28
       0 1932.29     9.8 1928.32    19.6 1923.38    29.4 1918.03    39.1 1912.91
    48.9 1908.34    58.7 1903.88    68.5 1899.14    78.3 1895.57      79  1895.5
      88 1894.64      94 1895.54    97.8 1896.11   107.6 1898.76   117.4 1901.19
   127.2 1902.67     137 1903.53   146.7 1903.82   156.5 1904.28   166.3 1905.52
   176.1 1907.52   185.9 1910.05   205.4  1915.5   215.2 1917.98     225 1920.14
   244.6 1924.14   254.4 1926.03   293.5 1933.28
#Mann= 3 ,-1 , 0
       0     .12       0      79    .045       0      94     .12       0
Bank Sta=79,94
XS Rating Curve= 0 ,0
Exp/Cntr=0.3,0.1

Type RM Length L Ch R = 1 ,27402.9 ,128.2,142.4,156.6
XS GIS Cut Line= 3
     1875323.785      252902.886     1875508.681      252982.314
      1875502.17      253053.928
#Sta/Elev= 23
       0 1909.32     9.6 1905.77    19.2 1901.95    28.8 1898.56    38.3 1895.84
    47.9 1893.73    57.5 1892.01    67.1 1890.73    76.7 1889.93    86.2 1889.44
   105.4 1889.06     115 1888.69  120.141888.272   124.6 1887.91   134.2 1887.38
  137.961888.167   143.7 1889.37   153.3 1895.45   162.9 1903.12   172.5 1908.35
   191.6 1914.25   201.2    1917   273.1 1932.17
#Mann= 3 ,-1 , 0
       0     .12       0  120.14    .045       0  137.96     .12       0
Bank Sta=120.14,137.96
XS Rating Curve= 0 ,0
Exp/Cntr=0.3,0.1

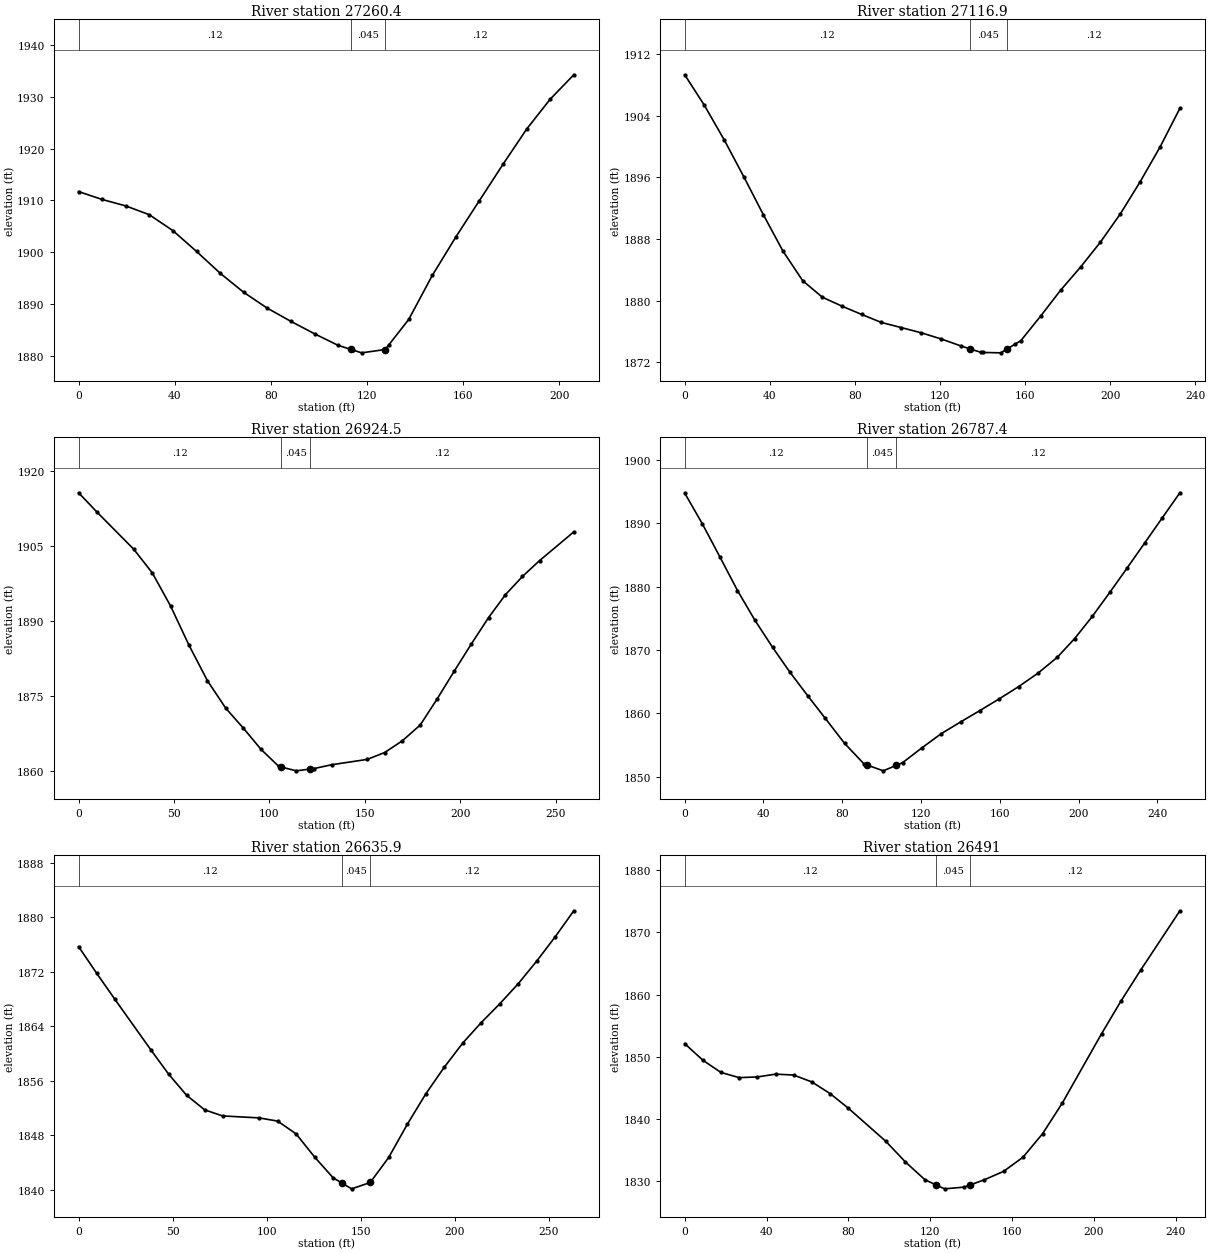
Type RM Length L Ch R = 1 ,27260.4 ,146,143.5,141
XS GIS Cut Line= 2
     1875286.025      252948.459     1875391.493      253125.543
#Sta/Elev= 25
       0  1911.7     9.8 1910.18    19.6 1908.94    29.4 1907.24    39.3 1904.14
    49.1 1900.13    58.9 1895.93    68.7 1892.24    78.5 1889.18    88.3 1886.64
    98.2 1884.22     108 1881.99  113.19 1881.22   114.2 1881.07   117.8 1880.54
   127.6 1881.18   129.2 1882.13   137.4    1887   147.2  1895.5     157 1902.93
   166.8 1909.96   176.7 1917.03   186.5  1923.8   196.3 1929.58   206.1 1934.28
#Mann= 3 ,-1 , 0
       0     .12       0  113.19    .045       0   127.6     .12       0
Bank Sta=113.19,127.6
XS Rating Curve= 0 ,0
Exp/Cntr=0.3,0.1

Type RM Length L Ch R = 1 ,27116.9 ,164.7,192.4,219.7
XS GIS Cut Line= 3
     1875190.973       252992.73     1875193.577      253085.178
     1875278.212      253197.157
#Sta/Elev= 30
       0 1909.29     9.2 1905.35    18.5 1900.88    27.8 1896.05      37 1891.12
    46.2 1886.41    55.5 1882.56    64.7 1880.43      74 1879.26    83.2 1878.19
    92.5 1877.15   101.8 1876.49   111.2 1875.81   120.6 1875.01   129.9  1874.1
  134.011873.737   139.3 1873.27   140.1 1873.26   148.6 1873.21  151.611873.715
   155.1  1874.3     158 1874.78   167.4    1878   176.7 1881.33   186.1 1884.34
   195.4 1887.56   204.8 1891.24   214.1  1895.4   223.5 1899.93   232.8 1904.94
#Mann= 3 ,-1 , 0
       0     .12       0  134.01    .045       0  151.61     .12       0
Bank Sta=134.01,151.61
XS Rating Curve= 0 ,0
Exp/Cntr=0.3,0.1

Type RM Length L Ch R = 1 ,26924.5 ,152.2,137.2,122
XS GIS Cut Line= 4
     1875071.181      253005.751     1875077.691      253082.574
     1875023.004      253168.511     1875042.535      253246.636
#Sta/Elev= 28
       0 1915.72     9.6 1911.86    28.9  1904.4    38.6 1899.66    48.2 1893.02
    57.8 1885.19    67.5 1878.05    77.1 1872.54    86.4 1868.51    95.6 1864.28
   104.9 1860.87   106.3 1860.73   114.1 1859.98   121.3 1860.34   123.4 1860.44
   132.7 1861.21   151.2 1862.27   160.4 1863.65   169.7 1866.02     179 1869.16
   187.9  1874.4   196.9    1880   205.8 1885.41   214.8 1890.69   223.7  1895.3
   232.6 1898.95   241.6 1902.14   259.5 1907.88
#Mann= 3 ,-1 , 0
       0     .12       0   106.3    .045       0   121.3     .12       0
Bank Sta=106.3,121.3
XS Rating Curve= 0 ,0
Exp/Cntr=0.3,0.1

Type RM Length L Ch R = 1 ,26787.4 ,155.9,151.4,147
XS GIS Cut Line= 4
     1874938.368      253010.959     1874920.139       253079.97
     1874931.858      253197.157     1874948.785      253257.053
#Sta/Elev= 30
       0 1894.74     8.9 1889.93    17.8 1884.72    26.8 1879.38    35.7 1874.67
    44.6 1870.44    53.5 1866.47    62.5 1862.78    71.4 1859.22    81.2 1855.28
      91 1852.06    92.5 1851.89   100.8 1850.96   107.5 1851.84   110.6 1852.24
   120.4 1854.58   130.3 1856.83   140.1 1858.67   149.9 1860.47   159.7 1862.31
   169.5 1864.23   179.3 1866.34   189.2 1868.87     198 1871.82   206.9 1875.29
   215.8 1879.08   224.7 1882.97   233.6 1886.91   242.5 1890.86   251.4 1894.79
#Mann= 3 ,-1 , 0
       0     .12       0    92.5    .045       0   107.5     .12       0
Bank Sta=92.5,107.5
XS Rating Curve= 0 ,0
Exp/Cntr=0.3,0.1

Type RM Length L Ch R = 1 ,26635.9 ,144.6,144.9,145.2
XS GIS Cut Line= 3
     1874791.233      253013.564     1874761.285      253094.293
     1874813.368      253263.564
#Sta/Elev= 27
       0 1875.68     9.6 1871.78    19.1 1868.03    38.3 1860.59    47.8 1857.01
    57.4 1853.89      67 1851.76    76.5 1850.87    95.9 1850.58   105.8 1850.11
   115.6 1848.23   125.5 1844.82   135.3 1841.79  140.081841.004   145.1 1840.18
     155 1841.11   164.8 1844.78   174.7 1849.64   184.5 1854.09   194.3 1857.99
   204.2 1861.56     214 1864.55   223.8 1867.29   233.7 1870.26   243.5 1873.57
   253.4 1877.16   263.2 1880.94
#Mann= 3 ,-1 , 0
       0     .12       0  140.08    .045       0     155     .12       0
Bank Sta=140.08,155
XS Rating Curve= 0 ,0
Exp/Cntr=0.3,0.1

Type RM Length L Ch R = 1 ,26491   ,125.7,124.5,123.1
XS GIS Cut Line= 3
     1874631.077      253051.324     1874625.868      253139.866
     1874668.837      253287.001
#Sta/Elev= 26
       0 1852.08     8.9  1849.4    17.7 1847.44    26.6  1846.6    35.5 1846.71
    44.4 1847.16    53.2 1847.02    62.1 1845.91      71 1844.04    79.8 1841.72
    98.3 1836.33   107.8 1833.02   117.4 1830.14  122.751829.322     127 1828.67
   136.6 1828.95  139.311829.275   146.2  1830.1   155.8 1831.48   165.3 1833.76
   174.9 1837.56   184.5 1842.48   203.7 1853.67   213.2 1858.94   222.8 1863.92
     242  1873.5
#Mann= 3 ,-1 , 0
       0     .12       0  122.75    .045       0  139.31     .12       0
Bank Sta=122.75,139.31
XS Rating Curve= 0 ,0
Exp/Cntr=0.3,0.1

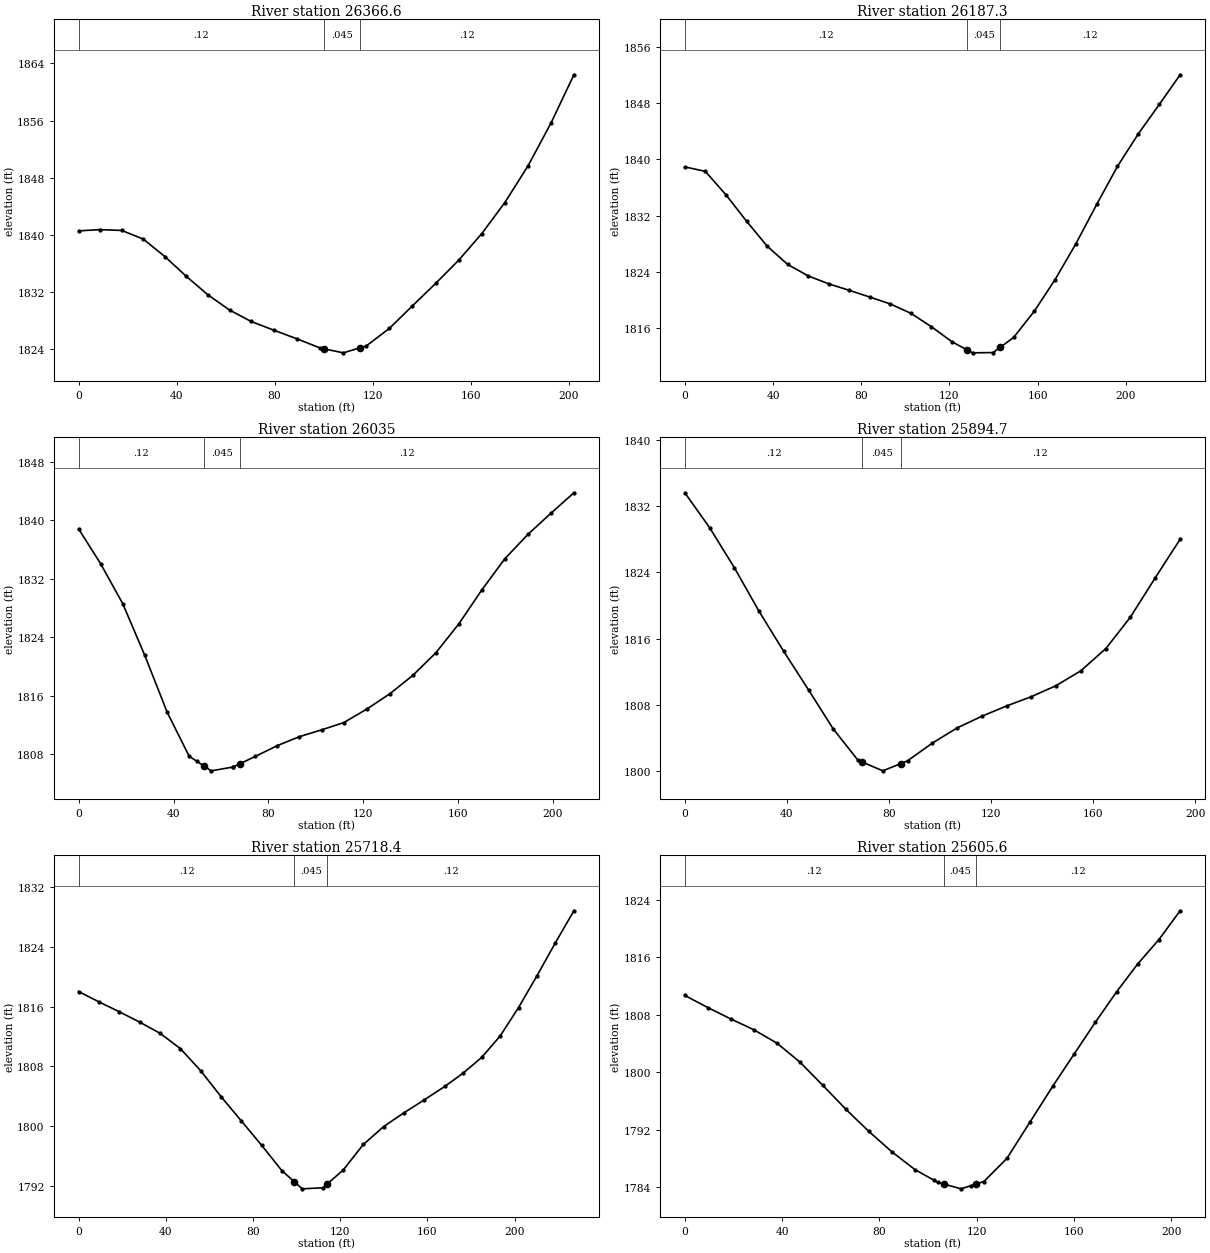
Type RM Length L Ch R = 1 ,26366.6 ,149.5,179.3,208.9
XS GIS Cut Line= 3
     1874501.476      253108.963     1874505.816      253179.275
     1874550.087      253303.407
#Sta/Elev= 25
       0 1840.58     8.8 1840.75    17.6 1840.64    26.4 1839.43    35.2 1836.99
      44 1834.21    52.8 1831.63    61.6 1829.51    70.4 1827.91    79.9 1826.66
    89.3 1825.46    98.7 1824.18     100 1824.09   108.1 1823.52     115 1824.24
   117.5  1824.5   126.9 1826.95   136.3  1830.1   145.8 1833.24   155.2 1836.49
   164.6  1840.2     174 1844.54   183.4 1849.63   192.8 1855.63   202.2 1862.41
#Mann= 3 ,-1 , 0
       0     .12       0     100    .045       0     115     .12       0
Bank Sta=100,115
XS Rating Curve= 0 ,0
Exp/Cntr=0.3,0.1

Type RM Length L Ch R = 1 ,26187.3 ,159.7,152.3,144.7
XS GIS Cut Line= 3
      1874464.15      253129.796     1874333.941      253220.074
     1874298.351      253275.847
#Sta/Elev= 27
       0 1838.94     9.3  1838.3    18.6 1834.98      28  1831.2    37.3 1827.66
    46.6 1825.04    55.9 1823.41    65.2 1822.27    74.6 1821.34    83.9 1820.38
    93.2  1819.4   102.5 1818.07   111.8 1816.16   121.2    1814     128 1812.85
   130.5 1812.43   139.8 1812.47     143 1813.21   149.1 1814.62   158.4 1818.33
   167.9 1822.86   177.4 1828.01   186.8  1833.6   196.2 1839.01   205.7 1843.67
   215.2 1847.85   224.6 1852.07
#Mann= 3 ,-1 , 0
       0     .12       0     128    .045       0     143     .12       0
Bank Sta=128,143
XS Rating Curve= 0 ,0
Exp/Cntr=0.3,0.1

Type RM Length L Ch R = 1 ,26035   ,162.9,140.3,117.1
XS GIS Cut Line= 3
     1874297.266      253040.386     1874231.077      253130.447
     1874240.842      253227.018
#Sta/Elev= 27
       0 1838.83     9.3 1834.06    18.6 1828.61    27.9 1821.53    37.3 1813.78
    46.6 1807.74    49.9 1807.03    52.91806.385    55.9 1805.74    64.9 1806.25
    65.2 1806.27   68.051806.714    74.5 1807.72    83.8 1809.19    93.1 1810.42
   102.4 1811.34   111.8 1812.34   121.5 1814.19   131.2 1816.28   140.9  1818.8
   150.6 1821.89   160.3 1825.85     170  1830.5   179.7 1834.76   189.4 1838.08
   199.1 1840.98   208.8 1843.78
#Mann= 3 ,-1 , 0
       0     .12       0    52.9    .045       0   68.05     .12       0
Bank Sta=52.9,68.05
XS Rating Curve= 0 ,0
Exp/Cntr=0.3,0.1

Type RM Length L Ch R = 1 ,25894.7 ,188.8,176.3,163.9
XS GIS Cut Line= 2
     1874106.294      253023.025     1874175.738      253204.232
#Sta/Elev= 23
       0 1833.59     9.7  1829.4    19.4 1824.57    29.1  1819.3    38.8 1814.46
    48.5 1809.82    58.2 1805.11    67.9 1801.34    69.6 1801.12    77.6 1800.07
    84.6 1800.94    87.3 1801.28      97 1803.41   106.7 1805.24   116.4 1806.65
   126.1 1807.89   135.8 1809.01   145.5 1810.34   155.2 1812.13     165 1814.81
   174.6 1818.59   184.4 1823.36   194.1 1827.98
#Mann= 3 ,-1 , 0
       0     .12       0    69.6    .045       0    84.6     .12       0
Bank Sta=69.6,84.6
XS Rating Curve= 0 ,0
Exp/Cntr=0.3,0.1

Type RM Length L Ch R = 1 ,25718.4 ,102.6,112.8,122.3
XS GIS Cut Line= 3
     1873900.131      253120.682     1874033.594      253222.678
     1874072.657      253267.166
#Sta/Elev= 28
       0 1818.04     9.3 1816.66    18.7 1815.32      28 1813.94    37.3 1812.45
    46.7 1810.38      56 1807.42    65.3 1803.96    74.7 1800.67      84  1797.4
    93.3    1794      99 1792.52   102.6 1791.58     112 1791.72     114 1792.23
   121.3 1794.08   130.6 1797.53     140 1799.94   149.3 1801.79   158.6 1803.52
     168 1805.32   176.4  1807.1   184.9 1809.21   193.4 1812.09   201.8 1815.89
   210.3 1820.17   218.7 1824.58   227.2 1828.87
#Mann= 3 ,-1 , 0
       0     .12       0      99    .045       0     114     .12       0
Bank Sta=99,114
XS Rating Curve= 0 ,0
Exp/Cntr=0.3,0.1

Type RM Length L Ch R = 1 ,25605.6 ,101.2,106.4,111.4
XS GIS Cut Line= 3
     1873863.021       253176.02     1873934.202      253309.701
     1873972.396      253345.291
#Sta/Elev= 27
       0 1810.71     9.5 1809.02    18.9 1807.44    28.4 1805.93    37.9 1804.06
    47.3 1801.44    56.8 1798.17    66.3 1794.83    75.7 1791.76    85.2 1788.91
    94.7 1786.43   102.6 1784.94   104.1 1784.66   106.61784.423   113.6 1783.76
   117.6 1784.19   119.71784.419     123 1784.78   132.5 1788.01     142 1793.09
   151.4  1798.1   160.2 1802.58   168.8 1806.95   177.6 1811.22   186.2 1815.07
     195  1818.5   203.7 1822.51
#Mann= 3 ,-1 , 0
       0     .12       0   106.6    .045       0   119.7     .12       0
Bank Sta=106.6,119.7
XS Rating Curve= 0 ,0
Exp/Cntr=0.3,0.1

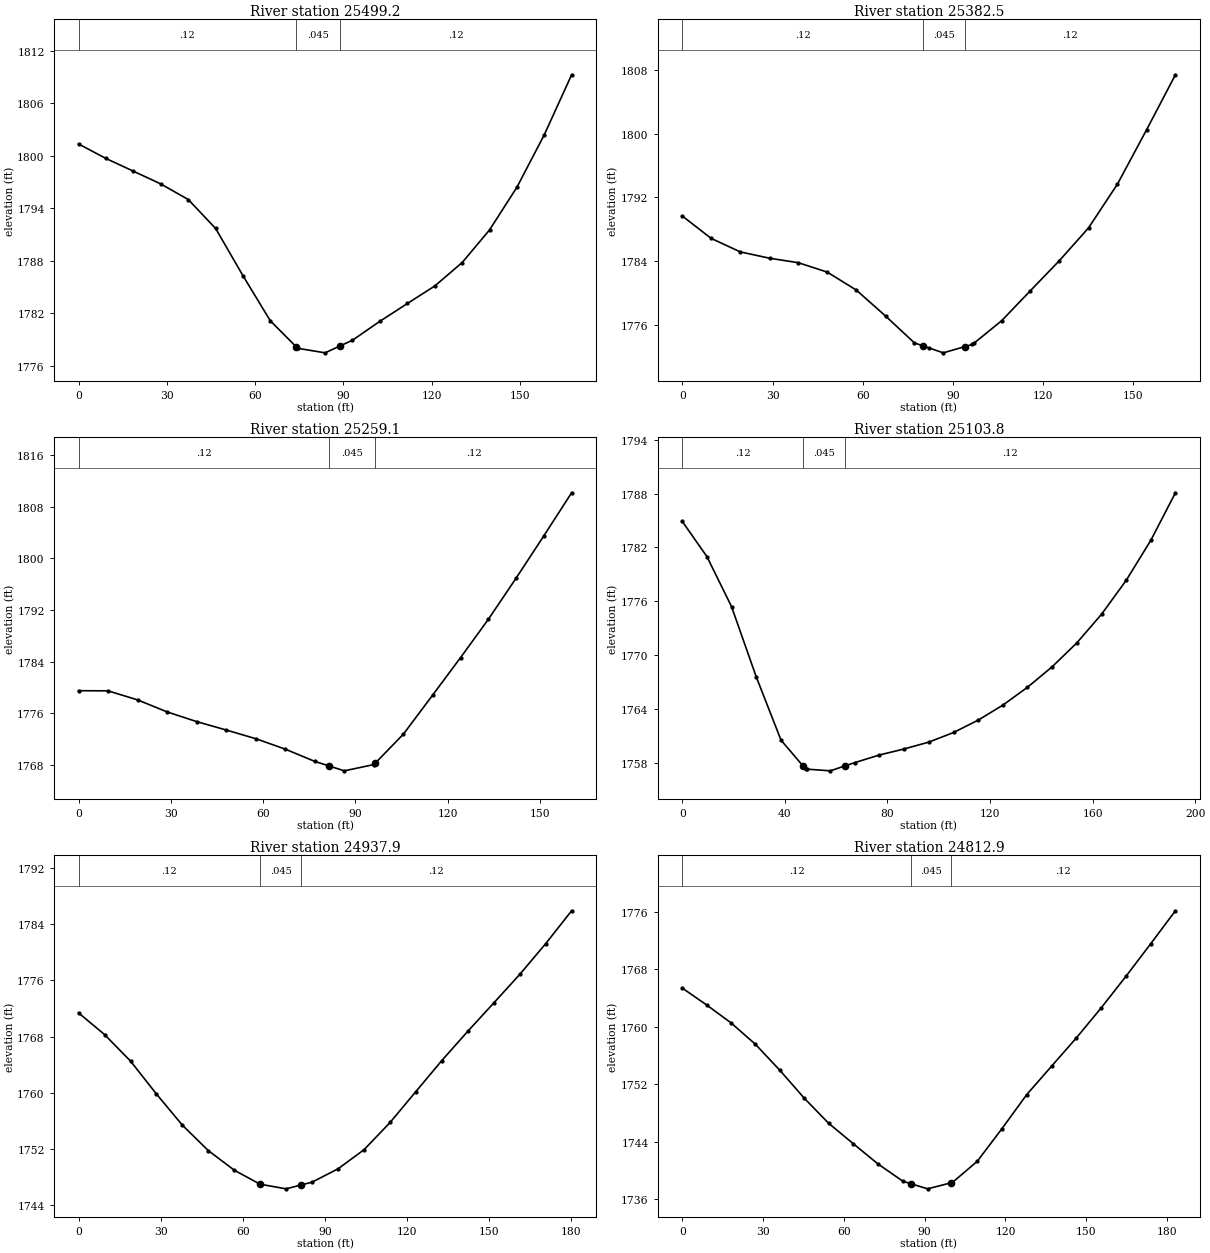
Type RM Length L Ch R = 1 ,25499.2 ,121.4,116.7,111.9
XS GIS Cut Line= 2
     1873794.445      253228.103     1873839.584      253389.562
#Sta/Elev= 21
       0 1801.36     9.3  1799.7    18.6 1798.25    27.9 1796.79    37.3    1795
    46.6 1791.69    55.9 1786.28    65.2 1781.12    73.9 1778.18    74.5 1777.98
    83.8 1777.46    88.9 1778.25    93.1  1778.9   102.4 1781.06   111.8 1783.11
   121.1 1785.11   130.4 1787.79   139.7 1791.52     149  1796.4   158.3  1802.4
   167.6 1809.27
#Mann= 3 ,-1 , 0
       0     .12       0    73.9    .045       0    88.9     .12       0
Bank Sta=73.9,88.9
XS Rating Curve= 0 ,0
Exp/Cntr=0.3,0.1

Type RM Length L Ch R = 1 ,25382.5 ,113.4,123.4,133.2
XS GIS Cut Line= 2
     1873667.492      253272.591     1873743.446      253417.991
#Sta/Elev= 22
       0 1789.66     9.6 1786.84    19.3 1785.14      29 1784.35    38.6 1783.78
    48.2  1782.6    57.9 1780.33    67.6 1777.07    77.2 1773.69   79.991773.324
      82 1773.06    86.8 1772.44    93.91773.216    96.5  1773.5      97 1773.65
   106.2 1776.48   115.8 1780.27   125.4 1784.04   135.1 1788.16   144.7 1793.66
   154.4  1800.5     164 1807.43
#Mann= 3 ,-1 , 0
       0     .12       0   79.99    .045       0    93.9     .12       0
Bank Sta=79.99,93.9
XS Rating Curve= 0 ,0
Exp/Cntr=0.3,0.1

Type RM Length L Ch R = 1 ,25259.1 ,154.9,155.3,155.5
XS GIS Cut Line= 3
     1873594.792      253318.164     1873600.217      253433.182
     1873618.663      253474.414
#Sta/Elev= 20
       0 1779.52     9.6  1779.5    19.2  1778.1    28.8 1776.24    38.4 1774.74
      48 1773.44    57.6  1772.1    67.2 1770.48    76.8 1768.58    81.5 1767.87
    86.4 1767.12      96 1768.09    96.5 1768.33   105.6 1772.79   115.2 1778.89
   124.2 1784.65   133.2 1790.55   142.2  1796.9   151.3 1803.51   160.3 1810.15
#Mann= 3 ,-1 , 0
       0     .12       0    81.5    .045       0    96.5     .12       0
Bank Sta=81.5,96.5
XS Rating Curve= 0 ,0
Exp/Cntr=0.3,0.1

Type RM Length L Ch R = 1 ,25103.8 ,173.9,165.9,157.9
XS GIS Cut Line= 3
     1873451.563      253304.058     1873455.903      253438.607
     1873472.179      253493.945
#Sta/Elev= 25
       0  1784.9     9.6 1780.98    19.2  1775.4    28.8 1767.59    38.5  1760.5
   47.141757.602    48.1 1757.28    48.6 1757.27    57.7 1757.08   63.541757.644
    63.6 1757.65    67.3    1758    76.9 1758.85    86.5 1759.52    96.2 1760.29
   105.8 1761.36   115.4 1762.74     125 1764.41   134.6  1766.4   144.2 1768.68
   153.8 1771.34   163.5 1774.55   173.1 1778.33   182.7 1782.79   192.3  1788.1
#Mann= 3 ,-1 , 0
       0     .12       0   47.14    .045       0   63.54     .12       0
Bank Sta=47.14,63.54
XS Rating Curve= 0 ,0
Exp/Cntr=0.3,0.1

Type RM Length L Ch R = 1 ,24937.9 ,125.7,125,124.6
XS GIS Cut Line= 2
     1873268.186      253333.355      1873335.46      253500.456
#Sta/Elev= 21
       0 1771.37     9.5 1768.29      19 1764.51    28.4 1759.86    37.9 1755.41
    47.4 1751.78    56.9 1748.99    66.3    1747    75.8 1746.34    81.3 1746.89
    85.3 1747.29    94.8 1749.19   104.3 1751.91   113.8 1755.78   123.2 1760.17
   132.7 1764.59   142.2 1768.76   151.7 1772.79   161.2 1776.86   170.6  1781.2
   180.1 1785.89
#Mann= 3 ,-1 , 0
       0     .12       0    66.3    .045       0    81.3     .12       0
Bank Sta=66.3,81.3
XS Rating Curve= 0 ,0
Exp/Cntr=0.3,0.1

Type RM Length L Ch R = 1 ,24812.9 ,181.6,199.6,216.9
XS GIS Cut Line= 3
      1873166.19      253359.397     1873165.104       253413.65
     1873216.103      253531.923
#Sta/Elev= 23
       0 1765.37       9 1763.03    18.1 1760.53    27.1 1757.57    36.2 1753.95
    45.2 1750.09    54.3 1746.58    63.5 1743.72    72.7  1740.9    81.9 1738.51
    84.9 1738.16    91.1 1737.45    99.9  1738.3   100.3 1738.34   109.5 1741.27
   118.7 1745.82   127.9 1750.56   137.1  1754.5   146.3 1758.43   155.5  1762.6
   164.7 1766.99   173.9 1771.52   183.1 1776.12
#Mann= 3 ,-1 , 0
       0     .12       0    84.9    .045       0    99.9     .12       0
Bank Sta=84.9,99.9
XS Rating Curve= 0 ,0
Exp/Cntr=0.3,0.1

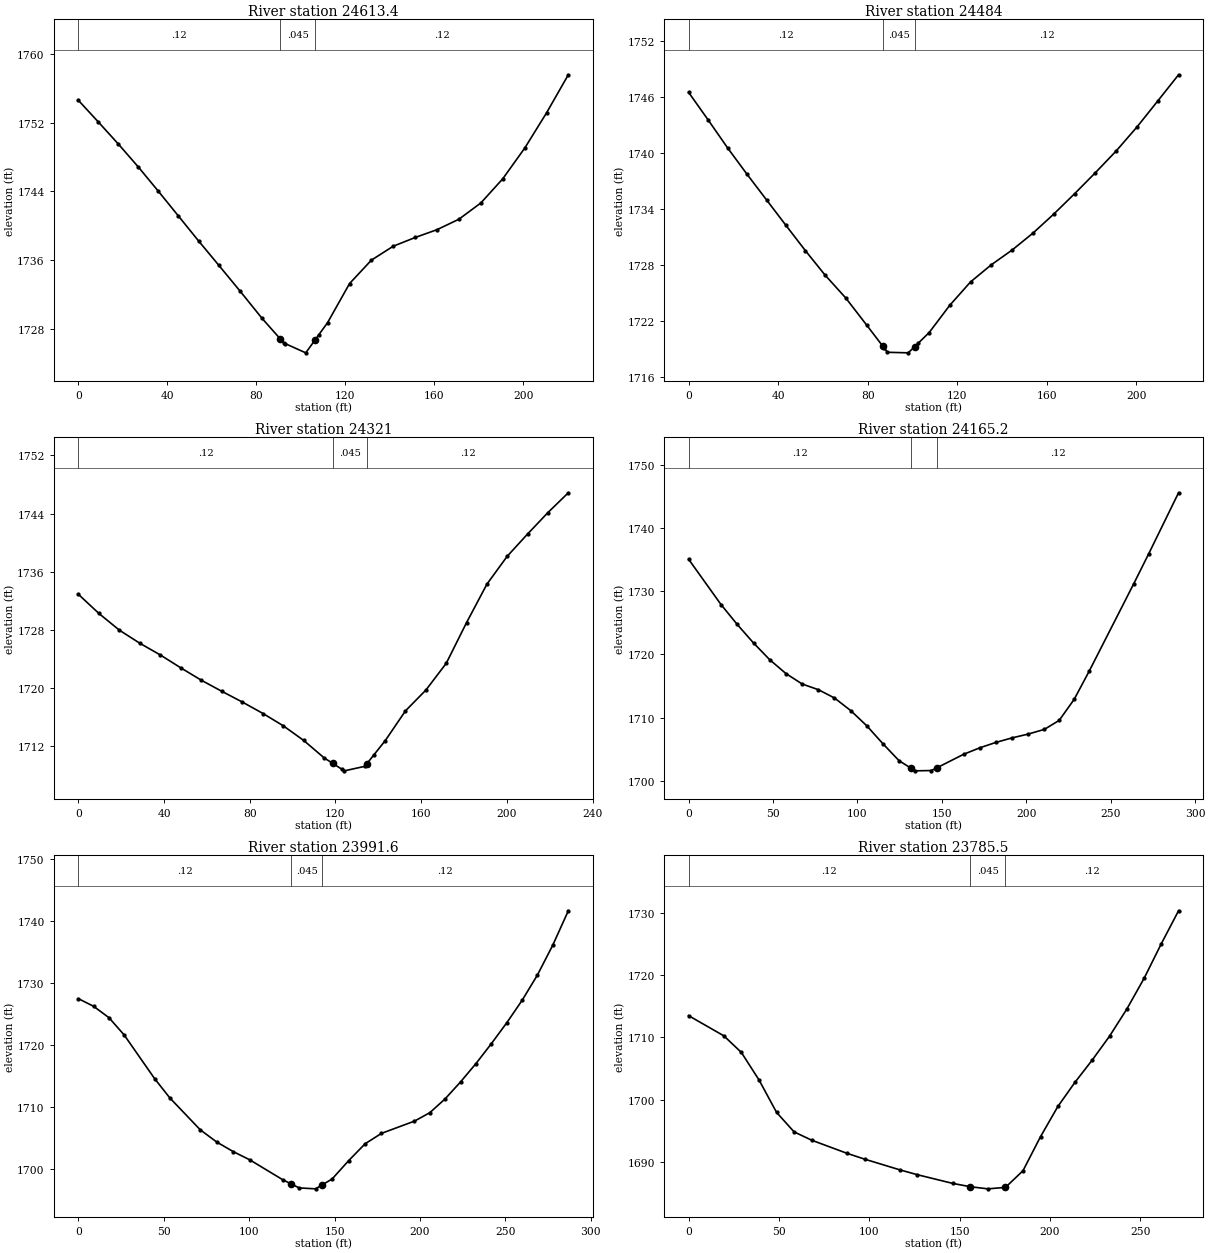
Type RM Length L Ch R = 1 ,24613.4 ,147.2,129.4,111.5
XS GIS Cut Line= 4
     1873007.769      253366.992     1873005.599      253429.926
     1872980.643      253493.945     1872991.493      253581.836
#Sta/Elev= 28
       0 1754.61       9 1752.08      18 1749.51      27 1746.83      36 1744.01
      45 1741.13      54 1738.25      63 1735.44    72.8 1732.36    82.6 1729.21
   90.751726.832    92.4 1726.35      93 1726.28   102.2 1725.21   106.41726.716
     108 1727.29     112 1728.72   121.9 1733.28   131.7    1736   141.5 1737.62
   151.4 1738.64   161.2 1739.55     171 1740.76   180.9 1742.66   190.7 1745.46
   200.6 1749.04   210.4 1753.14   220.2 1757.58
#Mann= 3 ,-1 , 0
       0     .12       0   90.75    .045       0   106.4     .12       0
Bank Sta=90.75,106.4
XS Rating Curve= 0 ,0
Exp/Cntr=0.3,0.1

Type RM Length L Ch R = 1 ,24484   ,165.7,163.1,160.4
XS GIS Cut Line= 3
     1872856.945      253381.098     1872852.604      253441.862
     1872916.624      253586.176
#Sta/Elev= 29
       0 1746.47     8.7 1743.53    17.4 1740.53    26.1  1737.7    34.8 1734.96
    43.5 1732.22    52.2 1729.51    60.9 1726.92    70.2 1724.45    79.5 1721.56
   86.711719.297    87.4 1719.08    88.8 1718.64    98.1 1718.58  100.911719.233
   102.4 1719.58   107.4 1720.74   116.6 1723.66   125.9 1726.17   135.2 1728.01
   144.5 1729.59   153.8  1731.4   163.1 1733.44   172.4 1735.62   181.6 1737.85
   190.9 1740.18   200.2 1742.75   209.5 1745.54   218.8 1748.35
#Mann= 3 ,-1 , 0
       0     .12       0   86.71    .045       0  100.91     .12       0
Bank Sta=86.71,100.91
XS Rating Curve= 0 ,0
Exp/Cntr=0.3,0.1

Type RM Length L Ch R = 1 ,24321   ,153.3,155.8,158.3
XS GIS Cut Line= 3
     1872676.823      253431.011      1872701.78      253513.477
     1872774.479       253636.09
#Sta/Elev= 29
       0 1732.89     9.6 1730.25    19.2 1727.94    28.7 1726.15    38.3 1724.53
    47.9 1722.75    57.4 1721.06      67 1719.53    76.6 1718.05    86.2 1716.48
    95.7 1714.78   105.2 1712.77   114.7 1710.38  118.821709.601   122.9 1708.83
   124.2 1708.59   133.7 1709.21  134.741709.596   137.9 1710.77   143.2 1712.73
   152.7 1716.85   162.2  1719.7   171.7 1723.38   181.2 1728.99   190.7 1734.28
   200.2 1738.13   209.7 1741.19   219.2 1744.14   228.7 1746.86
#Mann= 3 ,-1 , 0
       0     .12       0  118.82    .045       0  134.74     .12       0
Bank Sta=118.82,134.74
XS Rating Curve= 0 ,0
Exp/Cntr=0.3,0.1

Type RM Length L Ch R = 1 ,24165.2 ,198.8,173.6,148.1
XS GIS Cut Line= 4
     1872492.263      253502.268     1872549.281      253538.063
     1872608.464      253668.642     1872673.568      253714.215
#Sta/Elev= 29
       0 1735.08    19.2  1727.9    28.8 1724.75    38.5  1721.8    48.1 1719.15
    57.7 1716.96    67.3 1715.31    76.9 1714.41    86.4  1713.1      96 1711.11
   105.6 1708.68   115.1 1705.85   124.7 1703.16  131.861701.955   134.2 1701.56
   143.8 1701.61  146.851702.012   162.9 1704.18   172.5 1705.21     182 1706.06
   191.6 1706.78   201.1 1707.38   210.7 1708.12   219.5 1709.55   228.4 1712.89
   237.2 1717.31   263.7 1731.21   272.5 1735.92   290.2  1745.6
#Mann= 3 ,-1 , 0
       0     .12       0  131.86    .045       0  146.85     .12       0
Bank Sta=131.86,146.85
XS Rating Curve= 0 ,0
Exp/Cntr=0.3,0.1

Type RM Length L Ch R = 1 ,23991.6 ,187.4,206.1,224.8
XS GIS Cut Line= 4
     1872351.638      253699.316     1872415.874      253730.566
      1872541.19      253733.746     1872618.229      253780.404
#Sta/Elev= 30
       0 1727.44     8.9 1726.21    17.9 1724.38    26.8  1721.6    44.6 1714.57
    53.6 1711.43    71.4  1706.3    81.1 1704.32    90.7 1702.79   100.4 1701.46
   119.6 1698.27  124.741697.565   129.3 1696.94   138.9 1696.79  142.73 1697.42
   148.6 1698.38   158.2 1701.31   167.9 1704.05   177.5 1705.73   196.8  1707.7
   205.8 1709.06   214.8  1711.3   223.8 1714.02   232.8 1716.97   241.8 1720.17
   250.8 1723.53   259.8 1727.15   268.8 1731.24   277.8 1736.06   286.9  1741.6
#Mann= 3 ,-1 , 0
       0     .12       0  124.74    .045       0  142.73     .12       0
Bank Sta=124.74,142.73
XS Rating Curve= 0 ,0
Exp/Cntr=0.3,0.1

Type RM Length L Ch R = 1 ,23785.5 ,128.6,137.3,145.8
XS GIS Cut Line= 3
     1872324.728       253795.67     1872453.299      253942.079
     1872519.488      253980.057
#Sta/Elev= 25
       0 1713.47    19.5 1710.23    29.2 1707.57      39 1703.14    48.7 1697.94
    58.4 1694.81    68.2 1693.47    87.7 1691.37    97.4 1690.44   116.9 1688.72
   126.6 1687.94   146.1 1686.55   155.9 1686.01   165.6 1685.67   175.4  1685.9
   185.1 1688.58   194.8 1694.04   204.4 1698.89   213.9 1702.78   223.5 1706.37
     233 1710.17   242.5 1714.49   252.1 1719.44   261.6 1724.98   271.2  1730.3
#Mann= 3 ,-1 , 0
       0     .12       0   155.9    .045       0   175.4     .12       0
Bank Sta=155.9,175.4
XS Rating Curve= 0 ,0
Exp/Cntr=0.3,0.1

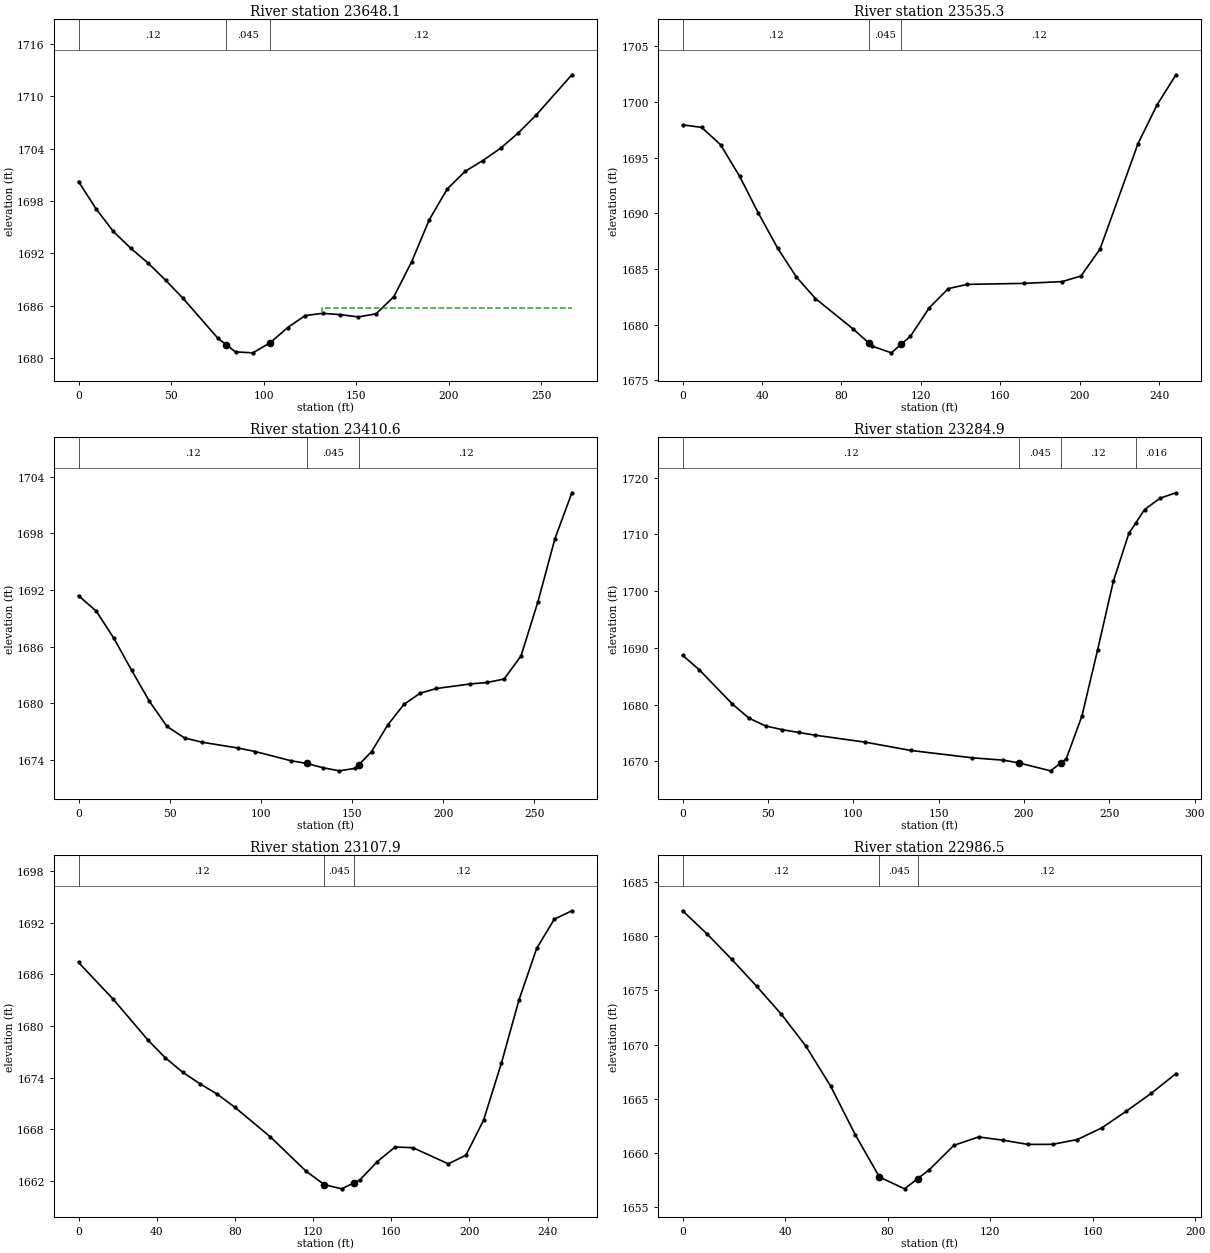
Type RM Length L Ch R = 1 ,23648.1 ,136.2,112.8,89
XS GIS Cut Line= 3
     1872273.177      253857.444      1872318.75      253981.142
     1872442.448       254034.31
#Sta/Elev= 28
       0 1700.22     9.4 1697.11    18.8  1694.5    28.2 1692.57    37.7 1690.85
    47.1 1688.89    56.5 1686.82    75.3 1682.25   79.861681.501    84.8 1680.69
    94.2 1680.58   103.6 1681.75     113 1683.48   122.4 1684.85   131.8 1685.11
   141.4 1684.96   151.1  1684.7   160.7 1685.05   170.3 1687.01   179.9    1691
   189.5 1695.85   199.2 1699.38   208.8 1701.38   218.4 1702.63     228 1704.04
   237.6  1705.8   247.2 1707.84   266.5 1712.46
#Mann= 3 ,-1 , 0
       0     .12       0   79.86    .045       0   103.6     .12       0
#XS Ineff= 2 , 0
                          131.58         1685.73
Permanent Ineff=
       F       F
Bank Sta=79.86,103.6
XS Rating Curve= 0 ,0
Exp/Cntr=0.3,0.1

Type RM Length L Ch R = 1 ,23535.3 ,141.3,124.7,107.4
XS GIS Cut Line= 2
     1872141.568      254016.156     1872386.025      254060.352
#Sta/Elev= 24
       0 1697.93     9.6  1697.7    19.1 1696.15    28.7 1693.32    38.2    1690
    47.8 1686.89    57.3 1684.28    66.9 1682.35      86  1679.6   93.751678.365
    95.6 1678.07   105.1 1677.48  110.021678.242   114.7 1678.96   124.2 1681.52
   133.8 1683.24   143.3 1683.62     172 1683.71   191.1 1683.87   200.6 1684.37
   210.2  1686.8   229.3 1696.24   238.9 1699.72   248.4 1702.42
#Mann= 3 ,-1 , 0
       0     .12       0   93.75    .045       0  110.02     .12       0
Bank Sta=93.75,110.02
XS Rating Curve= 0 ,0
Exp/Cntr=0.3,0.1

Type RM Length L Ch R = 1 ,23410.6 ,100.2,125.7,151.3
XS GIS Cut Line= 4
     1872121.603      254115.115      1872224.02      254170.289
     1872291.624      254127.626     1872365.408      254136.307
#Sta/Elev= 28
       0  1691.4     9.7 1689.77    19.4 1686.88    29.1  1683.5    38.8 1680.23
    48.5 1677.54    58.2 1676.31    67.9 1675.86    87.2 1675.26    96.9 1674.88
   116.3 1673.91   125.2 1673.61   134.1 1673.16     143 1672.83   151.9  1673.1
   153.9  1673.5   160.7 1674.86   169.6 1677.69   178.5 1679.88   187.4 1681.06
   196.3 1681.56   214.8 1682.04   224.1  1682.2   233.4 1682.56   242.7 1685.01
     252 1690.77   261.3 1697.44   270.6 1702.31
#Mann= 3 ,-1 , 0
       0     .12       0   125.2    .045       0   153.9     .12       0
Bank Sta=125.2,153.9
XS Rating Curve= 0 ,0
Exp/Cntr=0.3,0.1

Type RM Length L Ch R = 1 ,23284.9 ,147,177,206.9
XS GIS Cut Line= 4
     1872115.526      254141.156     1872208.408      254194.108
     1872239.998      254248.238     1872342.089      254310.427
#Sta/Elev= 24
       0 1688.71     9.7 1686.18    29.2 1680.12    38.9 1677.63    48.6 1676.27
    58.3 1675.61      68 1675.11    77.8 1674.63   106.9 1673.41   133.8 1671.94
   169.6 1670.65     188 1670.23   197.2 1669.74   215.6 1668.35  221.79 1669.76
   224.8 1670.45     234    1678   243.2 1689.66   252.4 1701.73   261.5 1710.18
  265.421711.974   270.7 1714.39   279.9 1716.41   289.1 1717.35
#Mann= 4 ,-1 , 0
       0     .12       0   197.2    .045       0  221.79     .12       0
  265.42    .016       0
Bank Sta=197.2,221.79
XS Rating Curve= 0 ,0
Exp/Cntr=0.3,0.1

Type RM Length L Ch R = 1 ,23107.9 ,122.5,121.4,120.3
XS GIS Cut Line= 4
     1872107.714      254153.309     1872136.471      254218.087
     1872108.247      254314.258     1872104.242      254395.497
#Sta/Elev= 25
       0 1687.37    17.7 1683.12    35.4  1678.4    44.3 1676.33    53.2 1674.65
      62 1673.31    70.9  1672.1      80 1670.56    98.2 1667.12   116.4 1663.15
   125.8 1661.58   134.6  1661.1   140.8 1661.77   143.8  1662.1   152.9 1664.27
     162 1665.96   171.1 1665.87   189.2    1664   198.2 1665.01   207.2 1669.06
   216.3 1675.65   225.3 1682.99   234.4 1689.01   243.4 1692.39   252.4 1693.37
#Mann= 3 ,-1 , 0
       0     .12       0   125.8    .045       0   140.8     .12       0
Bank Sta=125.8,140.8
XS Rating Curve= 0 ,0
Exp/Cntr=0.3,0.1

Type RM Length L Ch R = 1 ,22986.5 ,220.9,206.3,191.5
XS GIS Cut Line= 2
     1872021.776      254162.858     1871976.953      254350.065
#Sta/Elev= 22
       0 1682.35     9.6  1680.2    19.2 1677.86    28.9 1675.38    38.5 1672.81
    48.1 1669.86    57.8 1666.15    67.4 1661.67    76.8 1657.77    86.6 1656.68
    91.8 1657.63    96.2 1658.43   105.9  1660.7   115.5 1661.47   125.1 1661.17
   134.8 1660.78   144.4 1660.79     154 1661.23   163.6 1662.31   173.2 1663.86
   182.9  1665.5   192.5 1667.32
#Mann= 3 ,-1 , 0
       0     .12       0    76.8    .045       0    91.8     .12       0
Bank Sta=76.8,91.8
XS Rating Curve= 0 ,0
Exp/Cntr=0.3,0.1