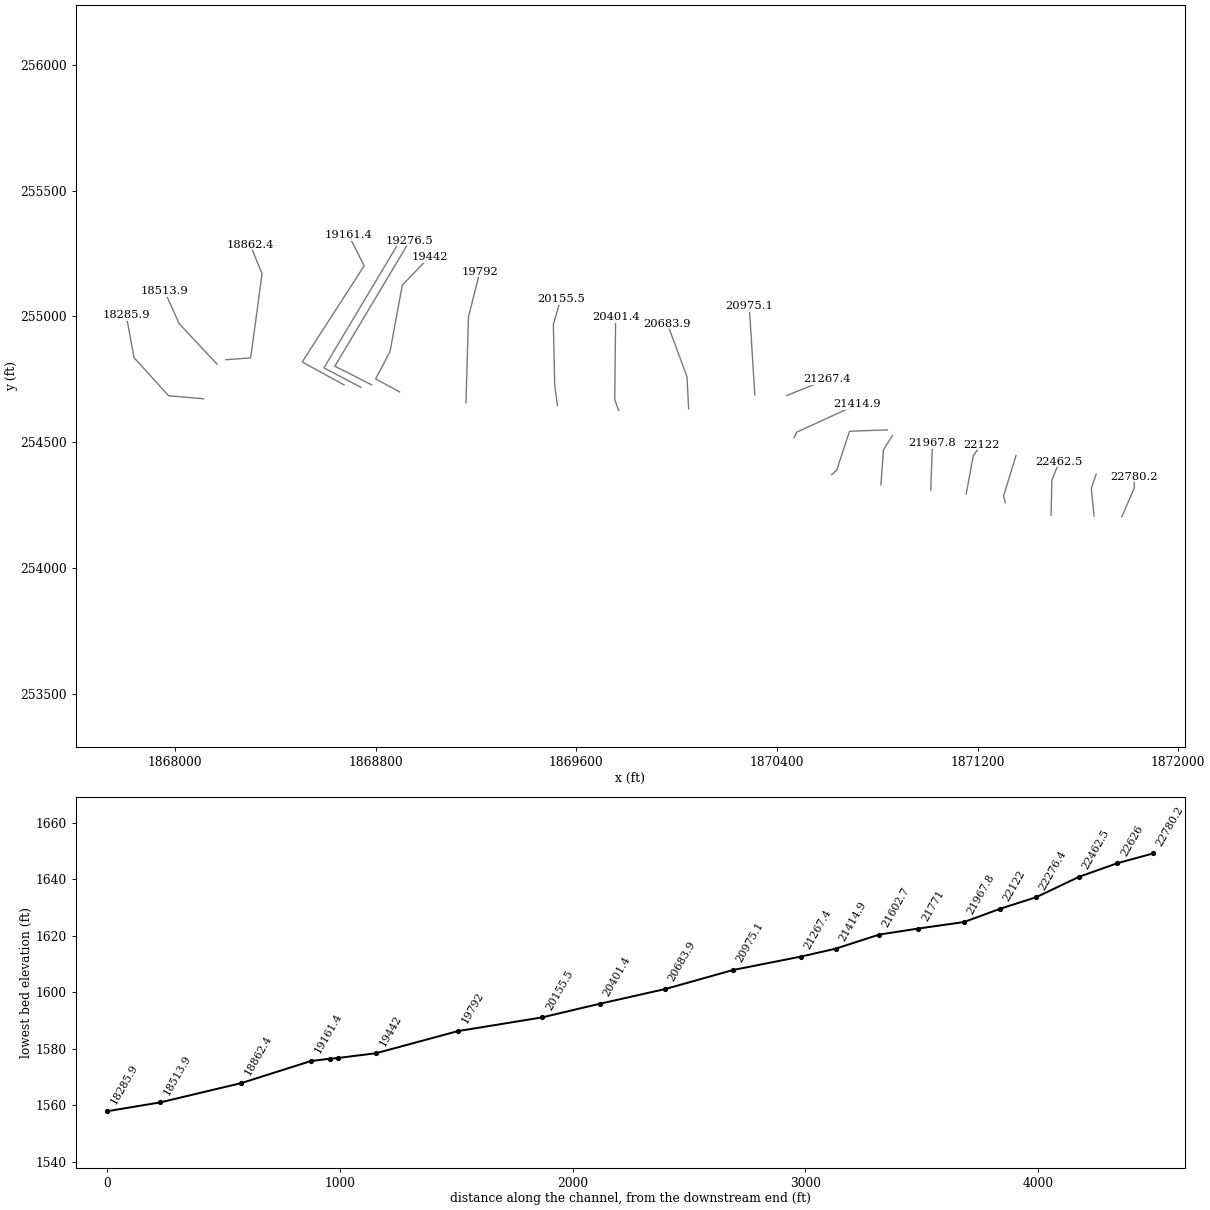
HEC-RAS study BUSHYFK.prj: BUSHYFK

--- BUSHYFK.g01 (geometry) --- (continued)

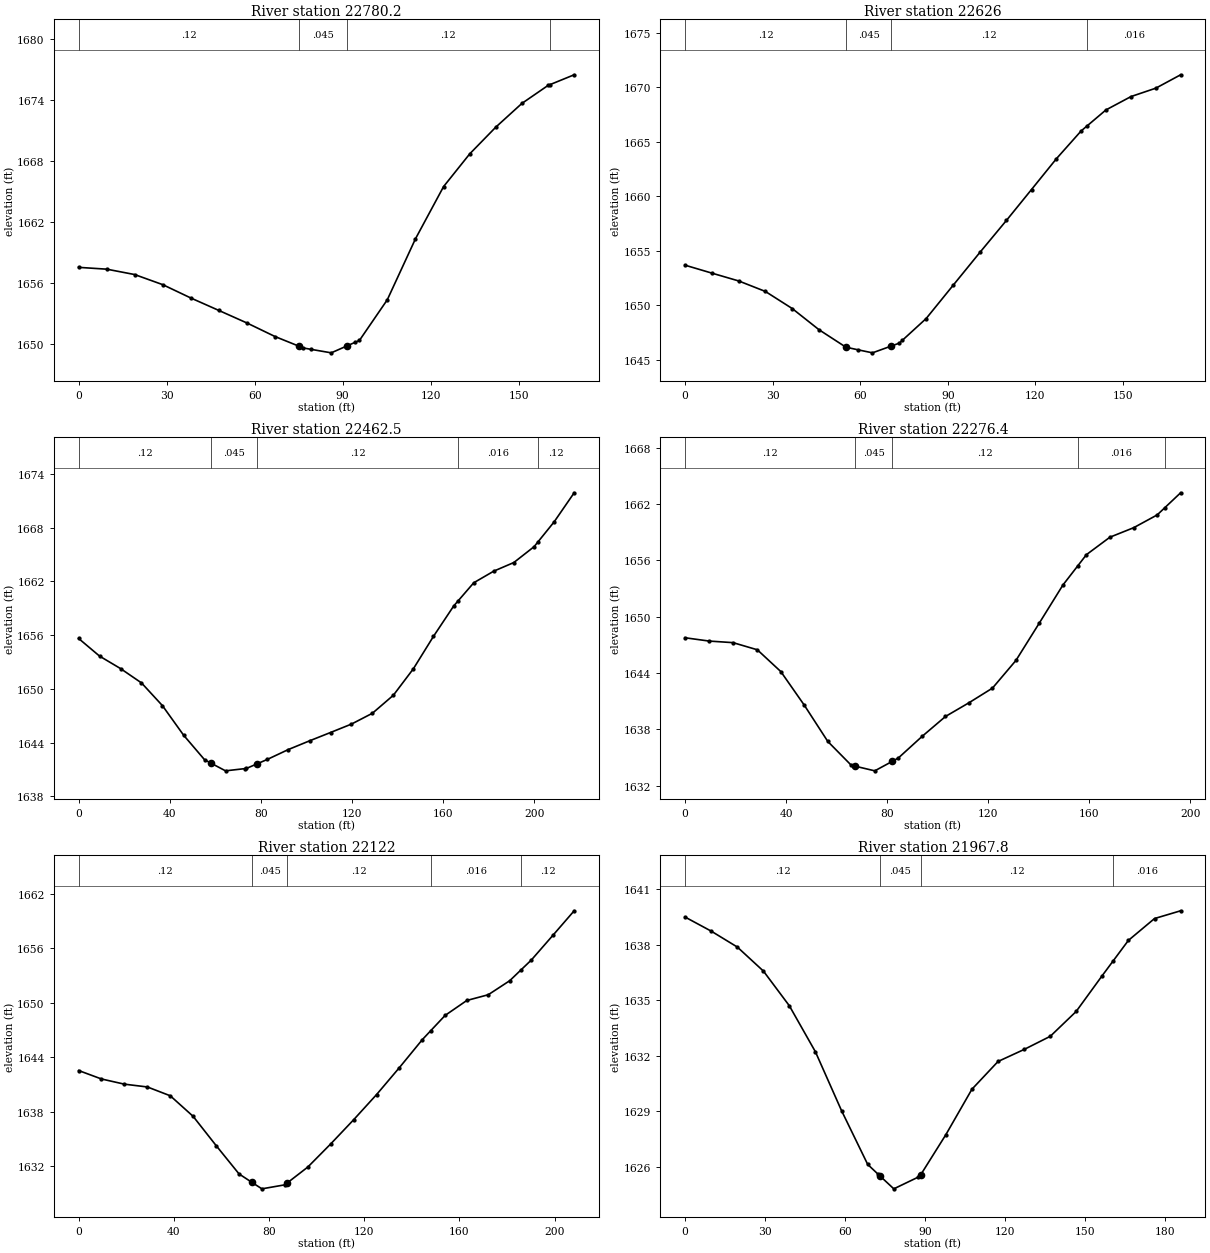
Type RM Length L Ch R = 1 ,22780.2 ,142.5,154.2,165.7
XS GIS Cut Line= 3
     1871775.131      254204.666     1871825.044      254318.598
     1871825.044      254363.086
#Sta/Elev= 24
       0 1657.51     9.6 1657.33    19.1  1656.8    28.7  1655.8    38.3 1654.48
    47.8 1653.26    57.4 1652.02      67 1650.68   74.961649.751    76.6 1649.56
    79.1 1649.43    86.1 1649.08   91.411649.757    94.1  1650.1    95.7  1650.3
   105.2 1654.31   114.8 1660.32   124.4 1665.48   133.3  1668.7   142.2 1671.34
   151.1 1673.68     160 1675.45   160.61675.521   168.9  1676.5
#Mann= 4 ,-1 , 0
       0     .12       0   74.96    .045       0   91.41     .12       0
   160.6    .016       0
Bank Sta=74.96,91.41
XS Rating Curve= 0 ,0
Exp/Cntr=0.3,0.1

Type RM Length L Ch R = 1 ,22626   ,166.3,163.6,160.8
XS GIS Cut Line= 3
     1871664.453      254207.921     1871653.603      254317.513
     1871673.134      254373.937
#Sta/Elev= 24
       0 1653.67     9.2 1652.94    18.4 1652.22    27.5 1651.26    36.7 1649.69
    45.9 1647.74    55.1 1646.14    59.4 1645.89    64.2 1645.62   70.621646.241
    73.4 1646.51    74.4 1646.76    82.6 1648.77    91.8 1651.81     101 1654.84
   110.1 1657.78   118.7 1660.62   127.2 1663.44   135.7    1666  137.86 1666.49
   144.2 1667.93   152.8 1669.16   161.3 1669.93   169.8 1671.16
#Mann= 4 ,-1 , 0
       0     .12       0    55.1    .045       0   70.62     .12       0
  137.86    .016       0
Bank Sta=55.1,70.62
XS Rating Curve= 0 ,0
Exp/Cntr=0.3,0.1

Type RM Length L Ch R = 1 ,22462.5 ,192.2,186,179.8
XS GIS Cut Line= 3
     1871493.079      254210.811     1871496.268       254348.98
     1871525.565      254422.765
#Sta/Elev= 30
       0 1655.62     9.2 1653.65    18.4 1652.26    27.6 1650.66    36.8 1648.12
    46.1 1644.82    55.3 1642.08    58.1  1641.7    64.5 1640.84    73.1 1641.09
    73.7 1641.11   78.421641.628    82.9 1642.12    92.1 1643.22   101.4 1644.19
   110.6 1645.12   119.8 1646.06     129 1647.27   138.2 1649.28     147 1652.24
   155.8 1655.85   164.7 1659.25  166.621659.815   173.5 1661.84   182.3 1663.14
   191.1  1664.1     200 1665.87  201.611666.377   208.8 1668.64   217.6 1671.89
#Mann= 5 ,-1 , 0
       0     .12       0    58.1    .045       0   78.42     .12       0
  166.62    .016       0  201.61     .12       0
Bank Sta=58.1,78.42
XS Rating Curve= 0 ,0
Exp/Cntr=0.3,0.1

Type RM Length L Ch R = 1 ,22276.4 ,151.8,154.4,157
XS GIS Cut Line= 3
     1871310.609      254259.998     1871303.993      254287.782
     1871353.473      254447.939
#Sta/Elev= 26
       0 1647.74     9.5 1647.39      19 1647.22    28.6 1646.46    37.9 1644.14
    47.2 1640.56    56.5  1636.7    65.8 1634.16    67.1 1634.08    75.1 1633.57
    82.1 1634.59    84.4 1634.93    93.8 1637.23   103.1 1639.36   112.4 1640.82
   121.7 1642.38     131 1645.33   140.3 1649.33   149.6 1653.36   155.41655.374
   158.9 1656.59   168.2 1658.45   177.6 1659.46   186.9 1660.82  190.011661.609
   196.2 1663.18
#Mann= 5 ,-1 , 0
       0     .12       0    67.1    .045       0    82.1     .12       0
   155.4    .016       0  190.01     .12       0
Bank Sta=67.1,82.1
XS Rating Curve= 0 ,0
Exp/Cntr=0.3,0.1

Type RM Length L Ch R = 1 ,22122   ,150.9,154.2,157.6
XS GIS Cut Line= 3
     1871154.702      254295.203       1871182.9      254446.636
      1871214.15      254490.907
#Sta/Elev= 27
       0 1642.52     9.6 1641.59    19.2 1641.02    28.9 1640.71    38.5 1639.74
    48.1 1637.48    57.8 1634.25    67.4 1631.14    72.7 1630.23      77  1629.5
    86.6 1629.94    87.7 1630.16    96.3  1631.9   105.9 1634.44   115.5 1637.09
   125.2 1639.88   134.8 1642.85   144.4 1645.92  147.881646.888     154 1648.59
   163.1 1650.23   172.1 1650.86   181.1  1652.4  185.81 1653.58   190.2 1654.68
   199.2 1657.38   208.2  1660.1
#Mann= 5 ,-1 , 0
       0     .12       0    72.7    .045       0    87.7     .12       0
  147.88    .016       0  185.81     .12       0
Bank Sta=72.7,87.7
XS Rating Curve= 0 ,0
Exp/Cntr=0.3,0.1

Type RM Length L Ch R = 1 ,21967.8 ,197.6,196.8,195.9
XS GIS Cut Line= 2
     1871013.425      254311.667     1871020.139      254497.418
#Sta/Elev= 25
       0  1639.5     9.8 1638.74    19.6 1637.88    29.4 1636.58    39.1 1634.71
    48.9 1632.22    58.7 1629.04    68.5 1626.14    72.4 1625.61   73.111625.515
    78.3 1624.82    87.4 1625.45      88 1625.49   88.341625.568    97.8 1627.74
   107.6  1630.2   117.4  1631.7   127.2 1632.35     137 1633.06   146.7  1634.4
   156.5 1636.34   160.71637.154   166.3 1638.24   176.1 1639.42   185.9 1639.84
#Mann= 4 ,-1 , 0
       0     .12       0   73.11    .045       0   88.34     .12       0
   160.7    .016       0
Bank Sta=73.11,88.34
XS Rating Curve= 0 ,0
Exp/Cntr=0.3,0.1

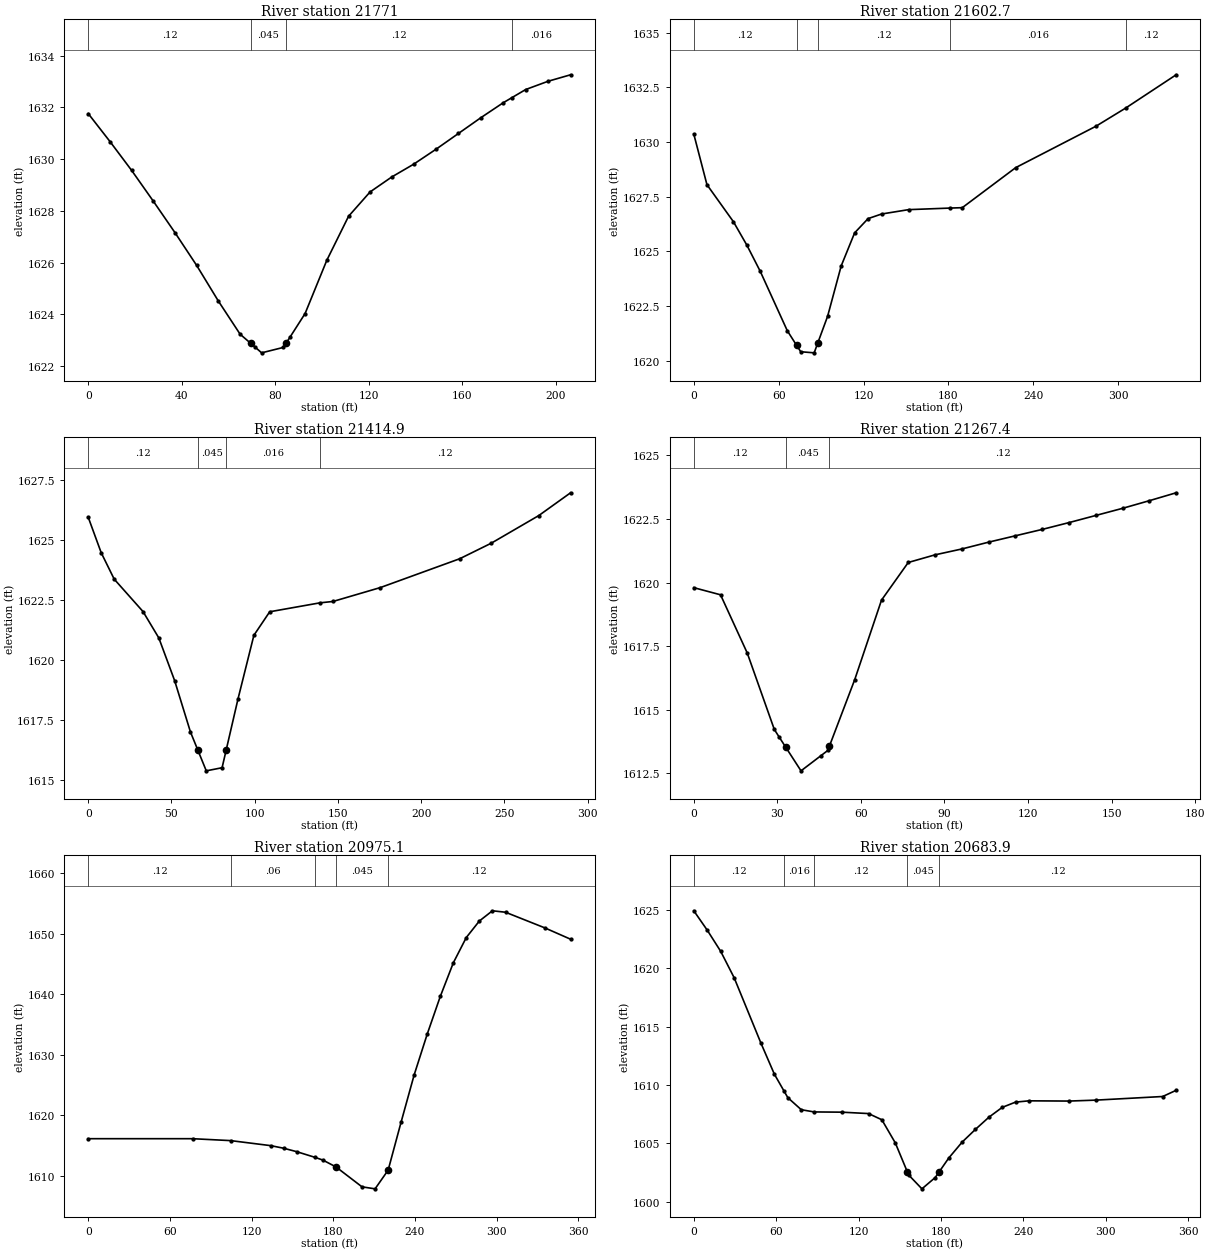
Type RM Length L Ch R = 1 ,21771   ,173.8,168.3,162.8
XS GIS Cut Line= 3
     1870814.618      254331.231     1870824.827      254470.074
     1870859.983      254527.366
#Sta/Elev= 28
       0 1631.76     9.3 1630.68    18.6 1629.56    27.8 1628.38    37.1 1627.16
    46.4 1625.89    55.7 1624.51      65 1623.23   69.561622.875    71.3 1622.74
    74.2 1622.51    83.5 1622.72   84.611622.875    86.3 1623.11    92.8 1624.03
   102.1 1626.09   111.4 1627.79   120.6 1628.73   129.9 1629.31   139.2  1629.8
   148.8 1630.38   158.4 1630.99     168  1631.6   177.6 1632.18  181.221632.372
   187.2 1632.69   196.8 1633.01   206.4 1633.26
#Mann= 4 ,-1 , 0
       0     .12       0   69.56    .045       0   84.61     .12       0
  181.22    .016       0
Bank Sta=69.56,84.61
XS Rating Curve= 0 ,0
Exp/Cntr=0.3,0.1

Type RM Length L Ch R = 1 ,21602.7 ,206.3,187.8,168.9
XS GIS Cut Line= 4
     1870618.292      254371.381     1870638.629      254390.647
      1870689.41      254544.293     1870840.452      254549.501
#Sta/Elev= 22
       0 1630.36     9.3 1628.05      28 1626.36    37.5 1625.29      47 1624.09
    66.1 1621.38    72.7 1620.71    75.6 1620.42    85.1 1620.37    87.7 1620.83
    94.6 1622.04   104.2 1624.34   113.7 1625.85   123.2  1626.5   132.7 1626.71
   151.8 1626.91  181.111626.982   189.8    1627   227.6 1628.83   284.3 1630.72
  305.371631.552     341 1633.07
#Mann= 5 ,-1 , 0
       0     .12       0    72.7    .045       0    87.7     .12       0
  181.11    .016       0  305.37     .12       0
Bank Sta=72.7,87.7
XS Rating Curve= 0 ,0
Exp/Cntr=0.3,0.1

Type RM Length L Ch R = 1 ,21414.9 ,148.6,147.5,146.4
XS GIS Cut Line= 3
      1870468.71      254519.139     1870478.473      254540.386
      1870720.66      254651.064
#Sta/Elev= 21
       0 1625.94     7.8 1624.46    15.6 1623.36    32.9 1622.01    42.4 1620.91
    51.9 1619.13    61.4 1616.99   65.861616.229    70.9 1615.37    80.4  1615.5
   82.841616.232      90 1618.38    99.5 1621.02     109    1622  139.131622.372
     147 1622.43   175.5 1623.01   223.1 1624.21   242.1 1624.86   270.6 1626.01
   289.7 1626.96
#Mann= 4 ,-1 , 0
       0     .12       0   65.86    .045       0   82.84    .016       0
  139.13     .12       0
Bank Sta=65.86,82.84
XS Rating Curve= 0 ,0
Exp/Cntr=0.3,0.1

Type RM Length L Ch R = 1 ,21267.4 ,263.3,292.3,320.5
XS GIS Cut Line= 2
     1870439.805      254686.458     1870600.769      254750.531
#Sta/Elev= 23
       0  1619.8     9.6 1619.52    19.2 1617.23    28.9 1614.23    30.7 1613.92
   33.021613.527    38.5  1612.6    45.7  1613.2    48.1  1613.4   48.721613.578
    57.8 1616.19    67.4 1619.31      77 1620.79    86.6 1621.09    96.2 1621.32
   105.9 1621.59   115.5 1621.84   125.1 1622.09   134.8 1622.36   144.4 1622.64
     154 1622.92   163.6 1623.22   173.2 1623.53
#Mann= 3 ,-1 , 0
       0     .12       0   33.02    .045       0   48.72     .12       0
Bank Sta=33.02,48.72
XS Rating Curve= 0 ,0
Exp/Cntr=0.3,0.1

Type RM Length L Ch R = 1 ,20975.1 ,284.6,291.2,297.8
XS GIS Cut Line= 2
     1870311.707      254688.031      1870289.67      255041.689
#Sta/Elev= 23
       0 1616.14    76.6 1616.14  104.671615.822   134.1 1614.99   143.6 1614.56
   153.2 1613.99  166.471613.063   172.4  1612.6     182 1611.47   201.1 1608.18
   210.7 1607.85   220.3 1610.94   229.8 1618.87   239.4 1626.68     249 1633.43
   258.6 1639.66   268.2 1645.23   277.7  1649.4   287.3 1652.13   296.9 1653.82
   306.5 1653.58   335.2 1651.01   354.3 1649.12
#Mann= 5 ,-1 , 0
       0     .12       0  104.67     .06       0  166.47     .12       0
     182    .045       0   220.3     .12       0
Bank Sta=182,220.3
XS Rating Curve= 0 ,0
Exp/Cntr=0.3,0.1

Type RM Length L Ch R = 1 ,20683.9 ,290.5,282.5,274
XS GIS Cut Line= 3
     1870047.818      254633.344     1870041.407      254760.439
     1869963.282      254970.508
#Sta/Elev= 30
       0 1624.91     9.8 1623.25    19.6 1621.44    29.4 1619.18    48.9 1613.59
    58.7 1610.93   65.691609.496    68.5 1608.92    78.3 1607.89   87.63  1607.7
   107.7 1607.68   127.3 1607.56     137 1607.03   146.8 1605.05  155.471602.601
   156.5 1602.31   166.2 1601.12   175.9 1602.09  178.91  1602.6   185.7 1603.75
   195.5 1605.12   205.2 1606.21     215 1607.25   224.7 1608.09   234.4 1608.54
   244.2 1608.65   273.4 1608.63   292.9 1608.71   341.6 1609.02   351.4 1609.55
#Mann= 5 ,-1 , 0
       0     .12       0   65.69    .016       0   87.63     .12       0
  155.47    .045       0  178.91     .12       0
Bank Sta=155.47,178.91
XS Rating Curve= 0 ,0
Exp/Cntr=0.3,0.1

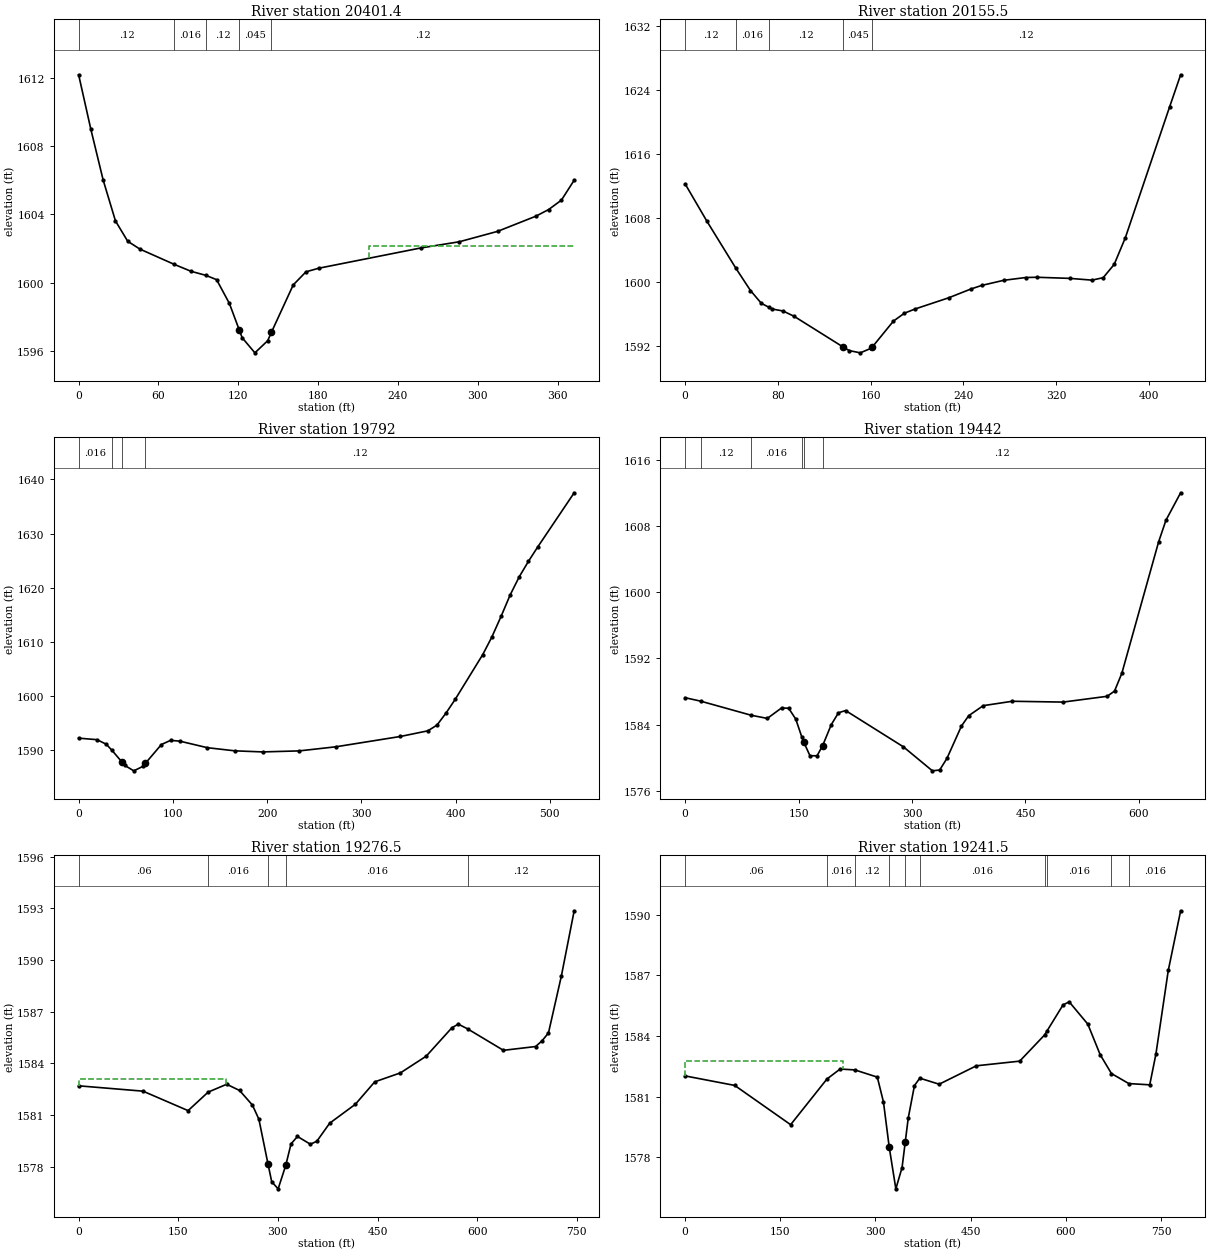
Type RM Length L Ch R = 1 ,20401.4 ,245.2,245.9,246.6
XS GIS Cut Line= 3
     1869768.837      254626.758     1869753.212      254670.161
     1869756.684       254996.55
#Sta/Elev= 26
       0 1612.19     9.2 1608.99    18.4 1606.03    27.7 1603.62    36.9 1602.43
    46.1 1601.97   71.931601.074    84.5 1600.67    95.61600.433   103.7 1600.18
   113.3 1598.79  120.891597.201   122.9 1596.78   132.5 1595.89   142.1  1596.6
  144.951597.099   161.3 1599.87   170.9 1600.64   180.5 1600.85   257.3 1602.04
   286.1  1602.4   314.9 1603.01   343.7  1603.9   353.3 1604.29   362.9 1604.84
   372.5 1606.01
#Mann= 5 ,-1 , 0
       0     .12       0   71.93    .016       0    95.6     .12       0
  120.89    .045       0  144.95     .12       0
#XS Ineff= 2 , 0
                          218.37         1602.14
Permanent Ineff=
       F       F
Bank Sta=120.89,144.95
XS Rating Curve= 0 ,0
Exp/Cntr=0.3,0.1

Type RM Length L Ch R = 1 ,20155.5 ,364.5,363.5,362.2
XS GIS Cut Line= 4
     1869524.495      254647.098     1869513.629      254730.925
      1869508.42      254968.772     1869537.934      255069.466
#Sta/Elev= 30
       0 1612.23    18.8 1607.56   43.821601.671    56.4 1598.89    65.7  1597.3
   72.111596.809    75.1 1596.58    84.5 1596.33      94 1595.67   136.61591.801
   141.6 1591.38   151.1  1591.1   160.7 1591.69   161.21591.782   179.7 1595.07
   189.2 1596.06   198.7  1596.6   227.3 1597.98   246.3 1599.07   255.8 1599.53
   274.8 1600.17   293.9 1600.52   303.4 1600.55     332 1600.41     351 1600.19
   360.6  1600.5   370.1 1602.16   379.7 1605.49   417.8 1621.82   427.4 1625.87
#Mann= 5 ,-1 , 0
       0     .12       0   43.82    .016       0   72.11     .12       0
   136.6    .045       0   161.2     .12       0
Bank Sta=136.6,161.2
XS Rating Curve= 0 ,0
Exp/Cntr=0.3,0.1

Type RM Length L Ch R = 1 ,19792   ,360.3,350.1,339.7
XS GIS Cut Line= 3
     1869159.793      254657.049     1869169.879      254998.286
     1869215.018      255177.105
#Sta/Elev= 30
       0 1592.25    19.5 1591.97    29.3 1591.13   35.111590.058    45.91587.861
    48.8 1587.24    58.5 1586.22    68.3 1587.05    70.91587.616    87.8 1591.07
    97.5 1591.84   107.3  1591.7   136.6 1590.49   165.8 1589.91   195.1 1589.71
   234.1  1589.9   273.1 1590.66   341.4 1592.56   370.5  1593.6   380.2 1594.65
   389.9  1596.9   399.6 1599.42   428.8 1607.67   438.4 1610.89   448.2  1614.7
   457.9 1618.68   467.6 1622.05   477.3 1624.88     487 1627.49   525.8 1637.52
#Mann= 4 ,-1 , 0
       0    .016       0   35.11     .12       0    45.9    .045       0
    70.9     .12       0
Bank Sta=45.9,70.9
XS Rating Curve= 0 ,0
Exp/Cntr=0.3,0.1

Type RM Length L Ch R = 1 ,19442   ,166.6,165.5,164.4
XS GIS Cut Line= 5
     1868895.269      254700.578     1868799.653      254752.192
     1868856.945      254860.265     1868906.037      255124.607
     1869014.192      255236.168
#Sta/Elev= 30
       0 1587.25   20.491586.835   87.481585.129   108.7 1584.75   127.5 1586.01
   136.9 1585.98   146.3 1584.67  154.171582.543   156.91581.888   165.1 1580.24
   174.5 1580.24   181.91581.476   193.3    1584   202.8 1585.43   212.2  1585.7
   288.6 1581.32     327 1578.42   336.6 1578.52   346.2 1579.92   365.4 1583.83
     375 1585.08   394.2 1586.29   432.6 1586.82   499.8 1586.72   558.1 1587.42
   567.8 1588.05   577.5 1590.21   626.1 1606.07   635.8 1608.68   655.2 1611.99
#Mann= 6 ,-1 , 0
       0     .06       0   20.49     .12       0   87.48    .016       0
  154.17     .12       0   156.9    .045       0   181.9     .12       0
Bank Sta=156.9,181.9
XS Rating Curve= 0 ,0
Exp/Cntr=0.3,0.1

Type RM Length L Ch R = 1 ,19276.5 ,35,34.9,34.9
XS GIS Cut Line= 3
     1868784.158      254728.355     1868637.095      254802.704
     1868936.067      255301.272
#Sta/Elev= 30
       0 1582.69    96.9 1582.38   164.8 1581.25     1951582.324   222.9 1582.78
   242.3 1582.42   261.7 1581.57   271.4 1580.75  285.241578.131   290.7 1577.12
   300.4 1576.71  311.851578.074   319.8 1579.32   329.5 1579.75   348.9  1579.3
   358.6 1579.47     378 1580.52   416.7 1581.62   445.8 1582.92   484.5 1583.44
   523.3 1584.41     562 1586.06   571.7 1586.27  586.081585.986   639.6 1584.75
     688 1584.97   697.7  1585.3   707.4 1585.76   726.8 1589.06   746.1 1592.85
#Mann= 5 ,-1 , 0
       0     .06       0     195    .016       0  285.24    .045       0
  311.85    .016       0  586.08     .12       0
#XS Ineff= 2 , 0
          221.26 1583.11
Permanent Ineff=
       F       F
Bank Sta=285.24,311.85
XS Rating Curve= 0 ,0
Exp/Cntr=0.3,0.1

Type RM Length L Ch R = 1 ,19241.5 ,81,80.1,79.3
XS GIS Cut Line= 3
     1868740.755      254718.807     1868593.521      254796.037
     1868910.026      255322.973
#Sta/Elev= 30
       0 1582.03    78.2 1581.56   166.3 1579.62  223.551581.877   244.3 1582.37
  267.571582.326   302.9 1581.97   312.6 1580.74  321.661578.512   332.1 1576.45
   341.9  1577.5   346.91578.757   351.6 1579.94   361.4 1581.55  369.811581.919
   400.4 1581.62     459 1582.53   527.3 1582.76  566.641584.058  570.321584.251
   595.6 1585.54   605.3 1585.69   634.6 1584.59   654.1 1583.08  671.841582.147
  699.291581.651   732.2 1581.59   741.9  1583.1   761.4 1587.24   780.9 1590.19
#Mann= 10 ,-1 , 0
       0     .06       0  223.55    .016       0  267.57     .12       0
  321.66    .045       0   346.9     .12       0  369.81    .016       0
  566.64     .12       0  570.32    .016       0  671.84     .12       0
  699.29    .016       0
#XS Ineff= 2 , 0
          249.33 1582.76
Permanent Ineff=
       F       F
Bank Sta=321.66,346.9
XS Rating Curve= 0 ,0
Exp/Cntr=0.3,0.1

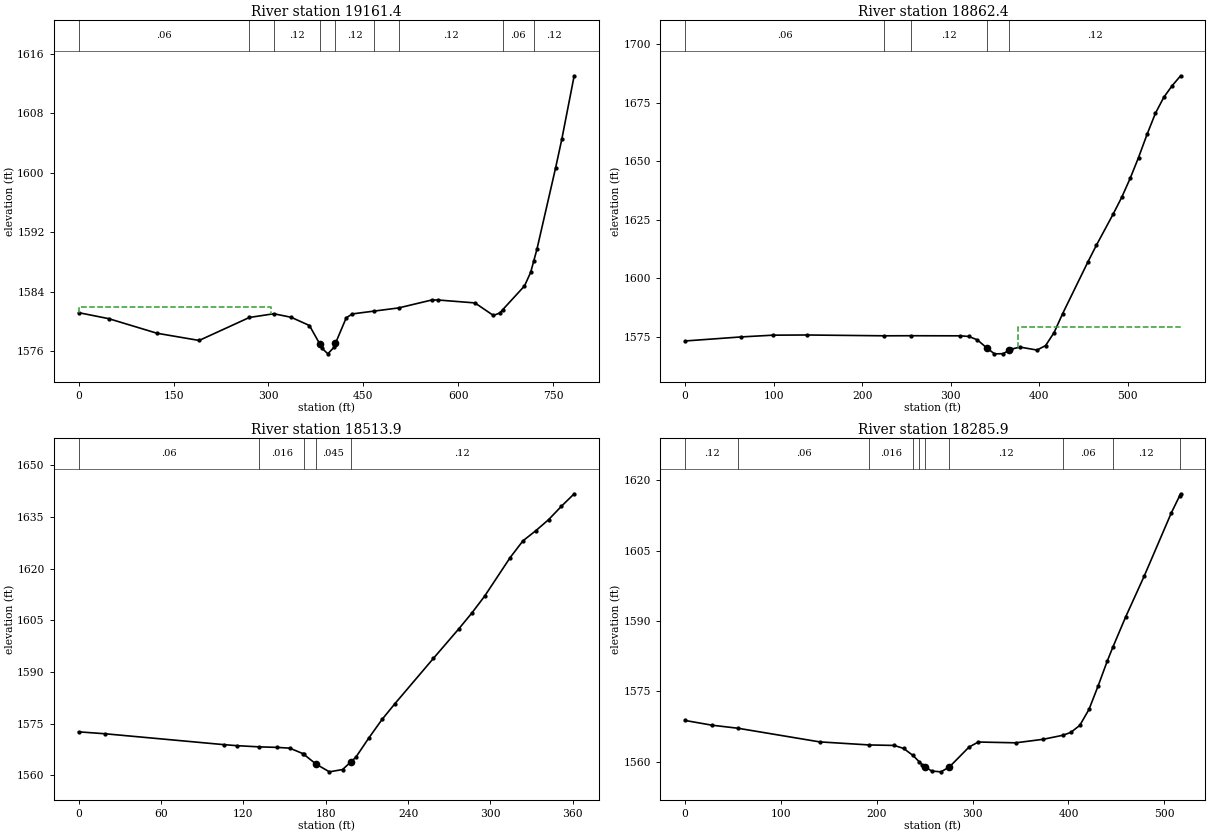
Type RM Length L Ch R = 1 ,19161.4 ,289,299,308.9
XS GIS Cut Line= 4
     1868673.915      254728.355      1868506.67      254819.313
      1868754.08      255201.411      1868691.58      255323.807
#Sta/Elev= 30
       0 1581.19    47.6 1580.38   123.8 1578.42   190.4 1577.45  269.821580.542
  308.351581.043   335.7 1580.57   364.7 1579.46   380.81577.011   384.1 1576.44
   393.8 1575.65   403.4 1576.53   405.81577.057   422.8 1580.49   432.5 1581.02
  466.171581.392  505.571581.825   558.4  1582.9   568.1 1582.89   626.2  1582.5
   655.4 1580.81   665.2 1581.14  670.121581.592   704.5 1584.78   714.3 1586.62
  718.941588.078   724.1  1589.7   753.6 1600.64   763.4 1604.49     783 1613.05
#Mann= 9 ,-1 , 0
       0     .06       0  269.82    .016       0  308.35     .12       0
   380.8    .045       0   405.8     .12       0  466.17     .06       0
  505.57     .12       0  670.12     .06       0  718.94     .12       0
#XS Ineff= 2 , 0
          304.64 1581.96
Permanent Ineff=
       F       F
Bank Sta=380.8,405.8
XS Rating Curve= 0 ,0
Exp/Cntr=0.3,0.1

Type RM Length L Ch R = 1 ,18862.4 ,328.3,348.5,368.6
XS GIS Cut Line= 4
      1868202.56      254828.182     1868301.495      254835.646
     1868346.615       255169.64      1868299.74      255284.223
#Sta/Elev= 30
       0 1573.34    63.1 1575.06    99.2 1575.81   137.7 1575.89  225.25 1575.54
  255.791575.575   311.1 1575.53   320.7 1575.26   330.3  1573.8   341.11570.321
   349.6 1567.85   359.2  1567.9   366.11569.309   368.8 1569.86   378.5 1570.73
   397.7 1569.46   407.4 1571.38     417 1576.93   426.6 1584.96   455.3 1607.12
   464.8 1614.18   483.9 1627.56   493.4  1634.6   502.9 1642.64   512.4 1651.56
     522  1661.4   531.5 1670.45     541 1677.28   550.5 1682.26     560 1686.44
#Mann= 5 ,-1 , 0
       0     .06       0  225.25    .016       0  255.79     .12       0
   341.1    .045       0   366.1     .12       0
#XS Ineff= 2 , 0
                          376.47         1579.16
Permanent Ineff=
       F       F
Bank Sta=341.1,366.1
XS Rating Curve= 0 ,0
Exp/Cntr=0.3,0.1

Type RM Length L Ch R = 1 ,18513.9 ,228.3,228,227.5
XS GIS Cut Line= 3
     1868167.375      254810.616     1868015.886      254971.723
     1867958.594      255099.327
#Sta/Elev= 27
       0 1572.64    19.2 1572.08   105.8 1568.92   115.4 1568.62  131.611568.273
   144.2 1568.13   153.8  1567.9   163.4 1566.31  164.151566.072   173.1 1563.23
   182.7 1561.02   192.3 1561.69   198.11563.837   201.9 1565.24   211.5 1570.91
   221.1 1576.27   230.5 1580.86   258.4 1593.95   277.1 1602.62   286.4 1607.12
   295.7 1612.01   314.4 1623.27   323.7 1628.12     333 1631.04   342.4 1634.28
   351.7 1638.15     361 1641.78
#Mann= 5 ,-1 , 0
       0     .06       0  131.61    .016       0  164.15     .12       0
   173.1    .045       0   198.1     .12       0
Bank Sta=173.1,198.1
XS Rating Curve= 0 ,0
Exp/Cntr=0.3,0.1

Type RM Length L Ch R = 1 ,18285.9 ,65.5,58.5,51.8
XS GIS Cut Line= 4
     1868113.962      254673.007     1867974.219      254685.265
     1867836.198      254836.307     1867804.948      255005.577
#Sta/Elev= 30
       0 1568.83    28.1 1567.82    55.11567.175   140.3 1564.27  192.271563.616
   218.2 1563.51     228 1562.87  237.75 1561.38  244.421560.004   247.4 1559.39
   250.71558.941   257.2 1558.06   266.9 1557.89   275.71558.923   296.2 1563.16
   305.9 1564.24   344.9 1564.07   373.6 1564.82     3941565.673   402.3 1566.27
   411.8 1567.79   421.4 1571.19     431 1576.23   440.5 1581.51  446.341584.467
   459.6 1590.86   478.8 1599.49   507.4 1613.09  516.09 1616.72     517  1617.1
#Mann= 10 ,-1 , 0
       0     .12       0    55.1     .06       0  192.27    .016       0
  237.75     .06       0  244.42     .12       0   250.7    .045       0
   275.7     .12       0     394     .06       0  446.34     .12       0
  516.09     .06       0
Bank Sta=250.7,275.7
XS Rating Curve= 0 ,0
Exp/Cntr=0.3,0.1