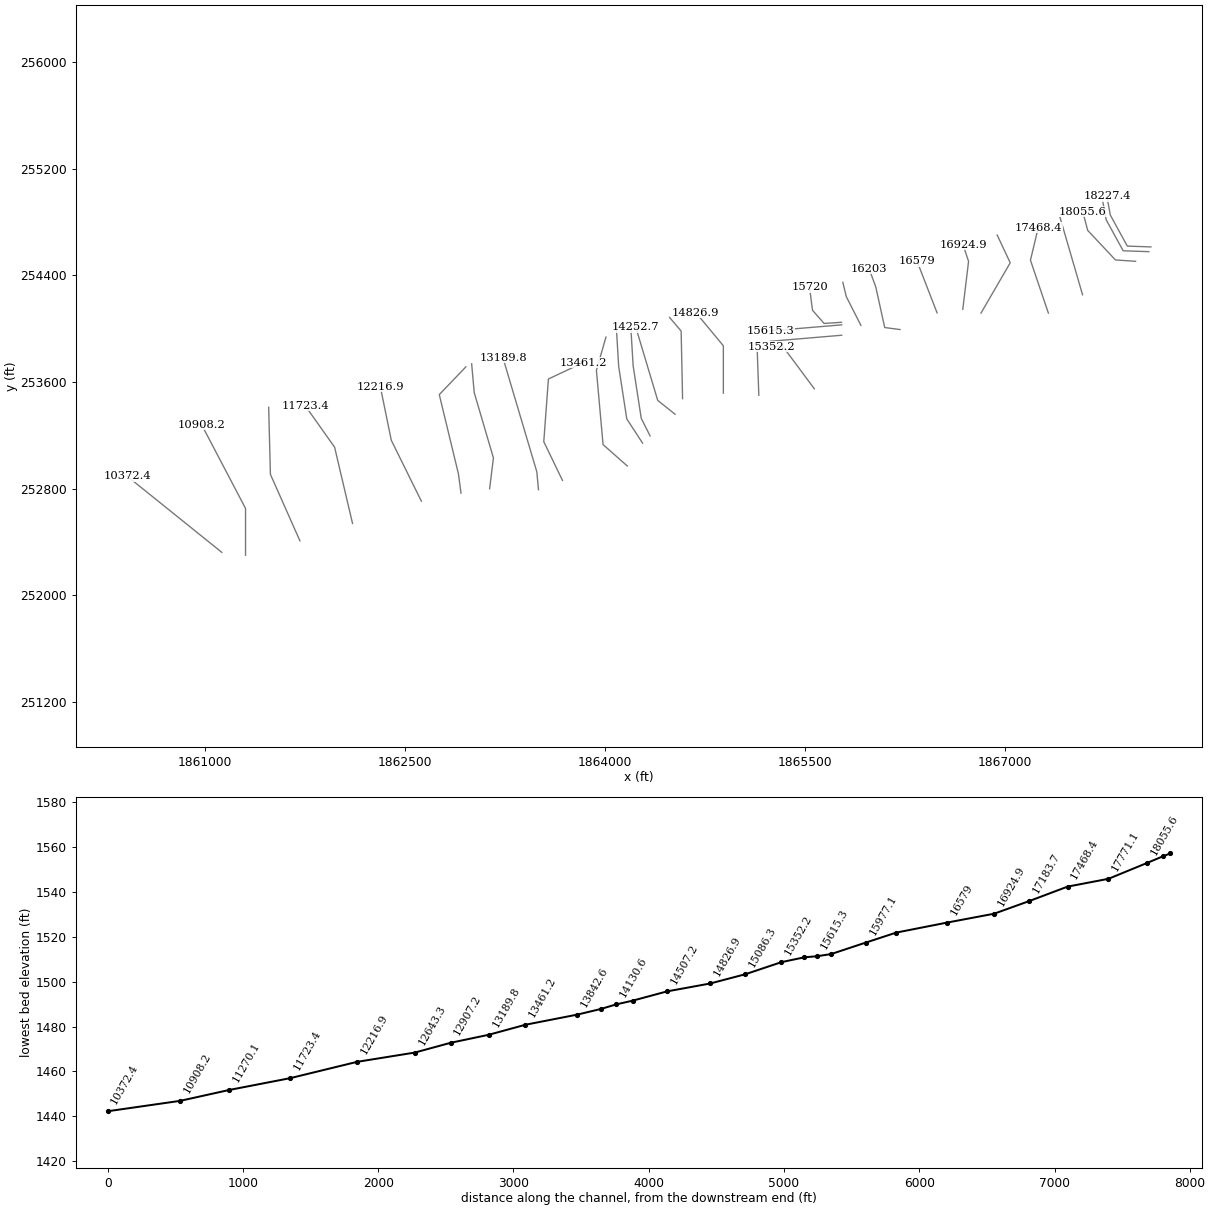
HEC-RAS study BUSHYFK.prj: BUSHYFK

--- BUSHYFK.g01 (geometry) --- (continued)

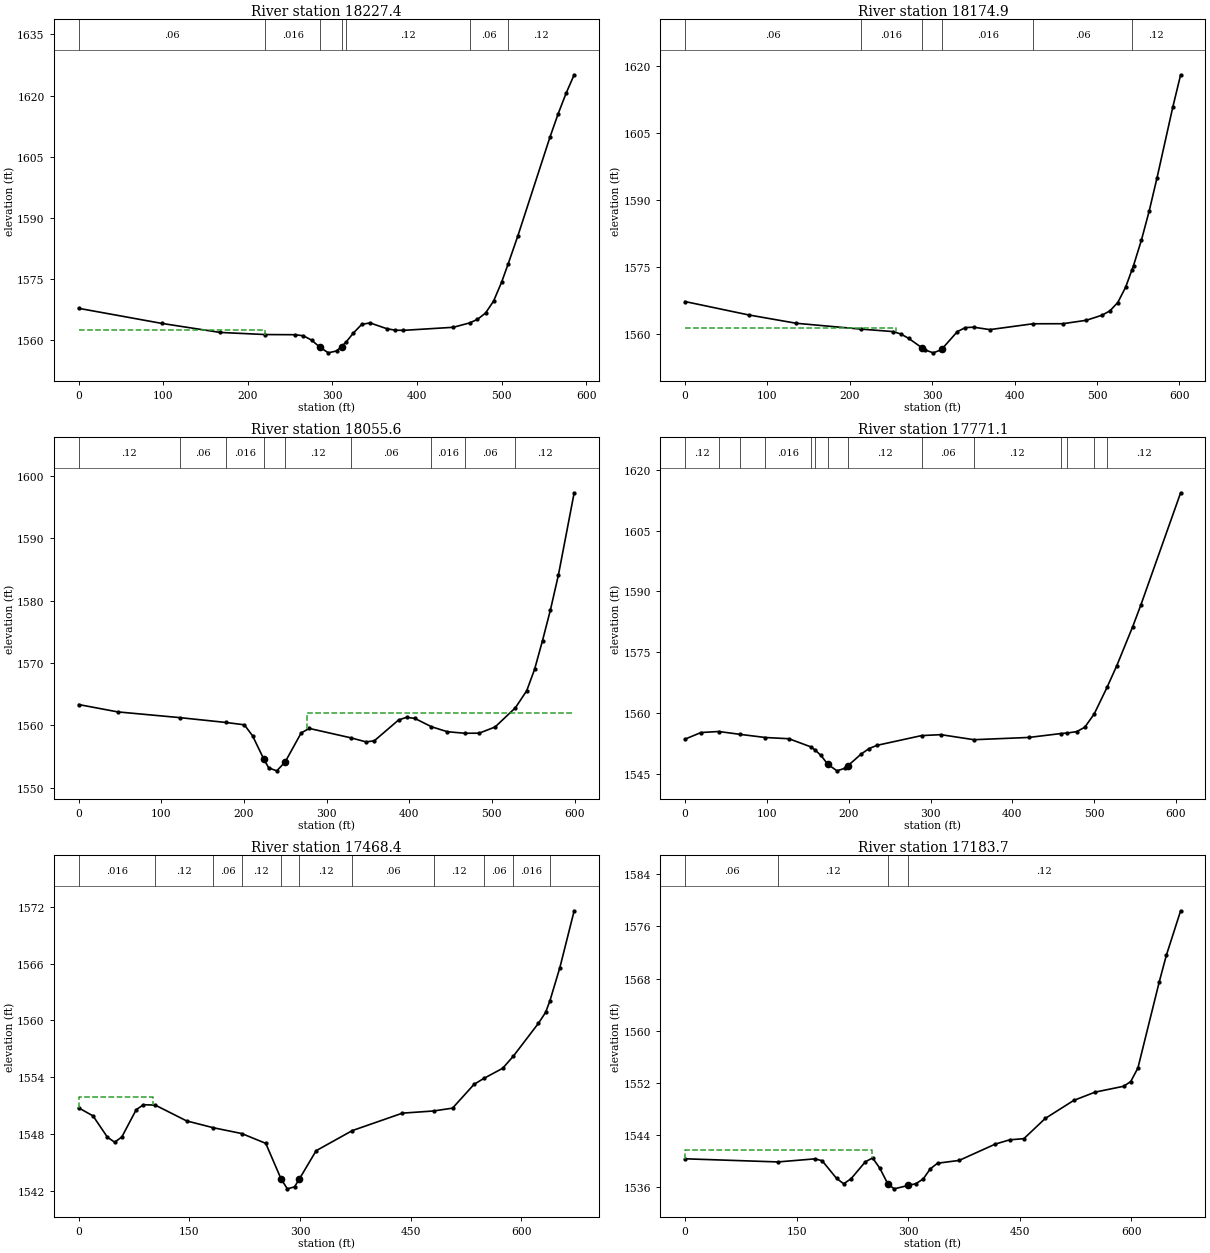
Type RM Length L Ch R = 1 ,18227.4 ,52.4,52.5,52.4
XS GIS Cut Line= 4
     1868096.441      254614.702     1867919.445      254620.682
     1867791.841      254853.755     1867765.799       254994.38
#Sta/Elev= 30
       0 1567.85    98.4 1564.15   167.3 1561.94  220.841561.419   255.8 1561.38
   265.7 1561.12   275.5 1560.04   285.4 1558.28   295.2 1556.94     305 1557.41
  310.761558.481  316.61 1559.69   324.7 1561.77   334.6  1563.9   344.4 1564.28
   364.1 1562.87   373.9  1562.5   383.8 1562.45   442.8  1563.2  462.251564.273
   471.4 1565.14     481 1566.68   490.5 1569.61     500 1574.25  507.891578.803
   519.1 1585.52   557.2 1609.81   566.8 1615.48   576.3 1620.58   585.8 1625.08
#Mann= 7 ,-1 , 0
       0     .06       0  220.84    .016       0   285.4    .045       0
  310.76    .016       0  316.61     .12       0  462.25     .06       0
  507.89     .12       0
#XS Ineff= 2 , 0
          220.43 1562.57
Permanent Ineff=
       F       F
Bank Sta=285.4,310.76
XS Rating Curve= 0 ,0
Exp/Cntr=0.3,0.1

Type RM Length L Ch R = 1 ,18174.9 ,111.9,119.4,126.4
XS GIS Cut Line= 4
     1868080.903      254579.015     1867888.195      254585.525
     1867760.591      254818.598     1867734.549      254959.223
#Sta/Elev= 30
       0 1567.19    77.1  1564.2     135 1562.33  213.281561.026   251.9 1560.48
   261.7 1559.95   271.6 1558.93   287.21556.886   291.2 1556.38   301.1 1555.71
   310.9 1556.37   312.21556.647   330.6 1560.48   340.4 1561.37   350.3 1561.45
     370 1560.91  422.371562.219   458.5 1562.23   487.1    1563   506.2 1564.14
   515.7 1565.11   525.3 1566.98   534.8  1570.4  542.261574.177   544.4 1575.26
   553.9 1580.89   563.4 1587.45     573 1594.95     592 1610.67   601.6 1617.97
#Mann= 6 ,-1 , 0
       0     .06       0  213.28    .016       0   287.2    .045       0
   312.2    .016       0  422.37     .06       0  542.26     .12       0
#XS Ineff= 2 , 0
          255.73 1561.35
Permanent Ineff=
       F       F
Bank Sta=287.2,312.2
XS Rating Curve= 0 ,0
Exp/Cntr=0.3,0.1

Type RM Length L Ch R = 1 ,18055.6 ,295,284.5,273.8
XS GIS Cut Line= 4
     1867981.163      254506.445     1867830.122      254516.862
     1867621.788      254739.084      1867585.33      254877.973
#Sta/Elev= 30
       0 1563.33    47.3 1562.15  122.251561.234  178.471560.452   200.5 1560.08
   210.4 1558.33  223.961554.606     230 1553.17   239.8  1552.7  249.981554.144
   269.3 1558.78   279.1  1559.5  329.241557.996   347.9 1557.34   357.8 1557.52
   387.2 1560.86     397 1561.29   406.9  1561.1  426.941559.769   446.2 1558.97
  467.451558.725   484.7 1558.74   503.9 1559.73  528.54 1562.82   542.2 1565.55
   551.7 1568.97   561.3 1573.59   570.9 1578.52   580.5 1584.08   599.6 1597.28
#Mann= 9 ,-1 , 0
       0     .12       0  122.25     .06       0  178.47    .016       0
  223.96    .045       0  249.98     .12       0  329.24     .06       0
  426.94    .016       0  467.45     .06       0  528.54     .12       0
#XS Ineff= 2 , 0
                          276.78         1561.91
Permanent Ineff=
       F       F
Bank Sta=223.96,249.98
XS Rating Curve= 0 ,0
Exp/Cntr=0.3,0.1

Type RM Length L Ch R = 1 ,17771.1 ,301.7,302.7,303.7
XS GIS Cut Line= 2
     1867583.449      254255.288     1867414.179      254836.885
#Sta/Elev= 30
       0 1553.51    19.5 1555.14   41.291555.386   67.231554.682   98.141553.904
     127  1553.6  153.681551.592   158.81550.833   166.1 1549.47   174.21547.338
   185.6 1545.67   195.4 1546.31   199.21546.958   214.9 1549.77   224.7 1551.16
   234.5 1551.97  289.051554.377   312.6 1554.61  353.011553.363   420.1 1553.92
  459.361554.883  467.29 1555.02   478.7 1555.36   488.5 1556.44  500.02 1559.71
  515.671566.268   527.6 1571.63   547.1 1581.29   556.9 1586.55   605.7 1614.37
#Mann= 14 ,-1 , 0
       0     .12       0   41.29     .06       0   67.23     .12       0
   98.14    .016       0  153.68     .06       0   158.8     .12       0
   174.2    .045       0   199.2     .12       0  289.05     .06       0
  353.01     .12       0  459.36     .06       0  467.29    .016       0
  500.02     .06       0  515.67     .12       0
Bank Sta=174.2,199.2
XS Rating Curve= 0 ,0
Exp/Cntr=0.3,0.1

Type RM Length L Ch R = 1 ,17468.4 ,303.6,284.7,265.1
XS GIS Cut Line= 3
     1867326.939      254117.701      1867192.39      254514.837
     1867250.984      254760.062
#Sta/Elev= 30
       0 1550.75    19.5  1549.9      39 1547.65    48.8 1547.12    58.5 1547.67
      78 1550.55    87.8 1551.08  103.771551.041   146.3 1549.37   182.4 1548.65
  220.911548.036   253.5    1547  274.38 1543.22   282.8 1542.19   292.5  1542.4
  299.011543.224   321.8 1546.22  370.741548.345   438.7 1550.19  480.83 1550.42
   506.6 1550.72   535.7 1553.23  549.151553.868   574.5 1554.93  588.941556.208
     623 1559.69   632.6 1560.83  638.281562.001     652 1565.57   671.4 1571.58
#Mann= 11 ,-1 , 0
       0    .016       0  103.77     .12       0   182.4     .06       0
  220.91     .12       0  274.38    .045       0  299.01     .12       0
  370.74     .06       0  480.83     .12       0  549.15     .06       0
  588.94    .016       0  638.28     .06       0
#XS Ineff= 2 , 0
          100.41 1551.94
Permanent Ineff=
       F       F
Bank Sta=274.38,299.01
XS Rating Curve= 0 ,0
Exp/Cntr=0.3,0.1

Type RM Length L Ch R = 1 ,17183.7 ,249.5,258.8,267.9
XS GIS Cut Line= 3
     1866821.297      254117.701     1867040.481      254495.305
     1866942.824      254703.639
#Sta/Elev= 30
       0 1540.35  124.781539.869   174.6 1540.34   184.4 1540.05   203.8 1537.34
   213.4 1536.52   223.2 1537.28   242.6  1539.9   252.3 1540.48     262  1538.9
   272.91536.466   281.4 1535.74  299.961536.259   310.5 1536.53   320.2 1537.24
   329.9 1538.81   339.6 1539.67   368.7  1540.1   417.2  1542.6   436.6 1543.26
   455.8 1543.44   484.5 1546.54   522.9 1549.31   551.6 1550.58     590 1551.48
   599.6 1552.21   609.2 1554.28   637.9 1567.49   647.5 1571.59   666.7 1578.41
#Mann= 4 ,-1 , 0
       0     .06       0  124.78     .12       0   272.9    .045       0
  299.96     .12       0
#XS Ineff= 2 , 0
          251.39 1541.66
Permanent Ineff=
       F       F
Bank Sta=272.9,299.96
XS Rating Curve= 0 ,0
Exp/Cntr=0.3,0.1

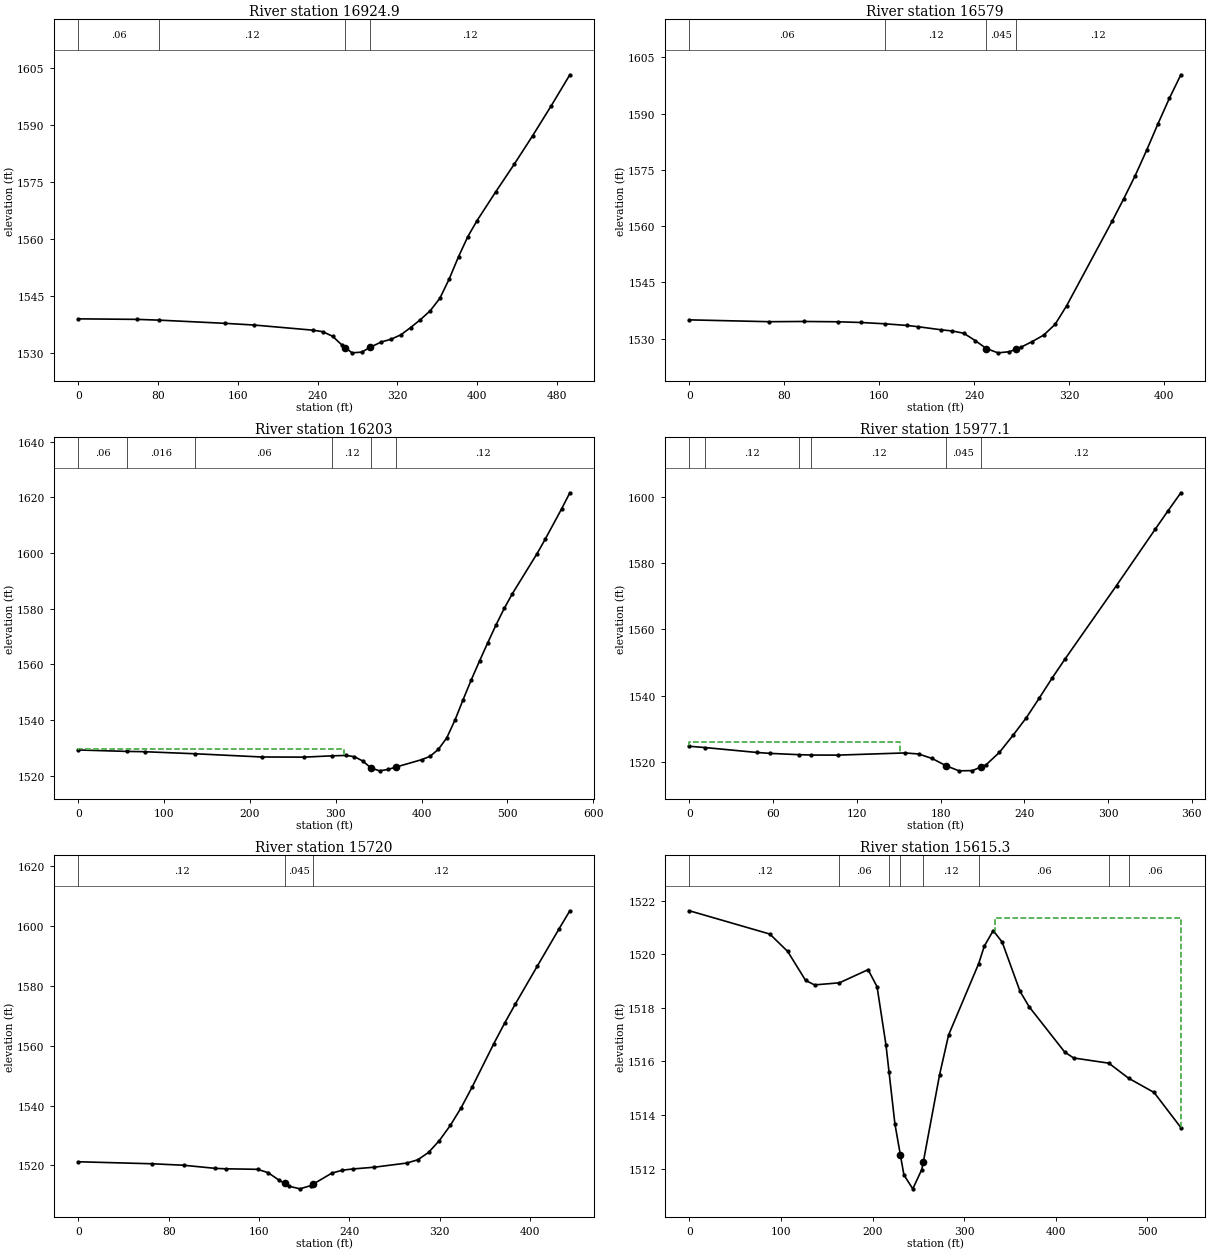
Type RM Length L Ch R = 1 ,16924.9 ,334.8,345.9,357
XS GIS Cut Line= 3
     1866684.578      254145.913     1866727.981      254506.156
     1866686.748      254629.854
#Sta/Elev= 29
       0 1539.08    58.8 1538.94   81.361538.737   147.1  1537.9   176.5 1537.45
   235.4  1536.1   245.2  1535.7     255 1534.51   264.8 1532.12   267.71531.533
   274.6 1530.14   284.4 1530.33   292.71531.584     304    1533   313.8 1533.72
   323.6 1534.88   333.4 1536.79   343.2 1538.86     353 1541.19   362.8 1544.51
   372.2 1549.62   381.5 1555.44   390.8  1560.7   400.1 1564.93   418.7 1572.44
   437.4 1579.75     456  1587.3   474.6 1595.15   493.2 1603.27
#Mann= 4 ,-1 , 0
       0     .06       0   81.36     .12       0   267.7    .045       0
   292.7     .12       0
Bank Sta=267.7,292.7
XS Rating Curve= 0 ,0
Exp/Cntr=0.3,0.1

Type RM Length L Ch R = 1 ,16579   ,379.4,375.9,372.4
XS GIS Cut Line= 2
     1866491.435      254119.871     1866341.696      254506.156
#Sta/Elev= 28
       0 1535.01    67.4 1534.52    96.4 1534.58   125.2  1534.5   144.5 1534.31
  164.731533.961   183.1 1533.53   192.7 1533.19     212 1532.37   221.6 1532.04
   231.2 1531.45   240.9  1529.5   250.31527.365   260.1 1526.22   269.8 1526.52
   275.31527.195   279.4  1527.7     289 1529.23   298.7 1530.95   308.3 1533.82
   317.9 1538.71   356.5 1561.39   366.1 1567.26   375.8 1573.45   385.4 1580.18
     395 1587.26   404.7 1594.12   414.3 1600.34
#Mann= 4 ,-1 , 0
       0     .06       0  164.73     .12       0   250.3    .045       0
   275.3     .12       0
Bank Sta=250.3,275.3
XS Rating Curve= 0 ,0
Exp/Cntr=0.3,0.1

Type RM Length L Ch R = 1 ,16203   ,220.2,226,231.7
XS GIS Cut Line= 4
     1866213.658      253994.003      1866098.64      254009.194
     1866031.366      254315.184     1865981.453      254449.733
#Sta/Elev= 30
       0 1529.26   56.191528.751    77.3 1528.63  136.361527.899   213.9 1526.74
   262.9 1526.69  295.581527.158   311.8  1527.3   321.6 1526.86   331.4  1525.3
   341.2 1522.76     351 1521.77   360.8 1522.26   370.6 1523.17   399.9 1525.76
   409.7 1526.95   419.5 1529.46   429.3 1533.58   438.9 1539.98   448.4 1547.33
     458 1554.51   467.6 1561.25   477.2 1567.81   486.7 1574.12   496.3 1580.07
   505.8 1585.36   534.6 1599.76   544.1 1604.94   563.3 1615.88   572.8  1621.6
#Mann= 6 ,-1 , 0
       0     .06       0   56.19    .016       0  136.36     .06       0
  295.58     .12       0   341.2    .045       0   370.6     .12       0
#XS Ineff= 2 , 0
          308.98 1529.73
Permanent Ineff=
       F       F
Bank Sta=341.2,370.6
XS Rating Curve= 0 ,0
Exp/Cntr=0.3,0.1

Type RM Length L Ch R = 1 ,15977.1 ,251.4,257,262.7
XS GIS Cut Line= 3
     1865919.734      254025.861     1865810.359      254241.139
     1865784.317      254348.778
#Sta/Elev= 25
       0 1524.73   11.321524.338    48.3 1522.86      58 1522.58   78.631522.193
   87.231522.088   106.2 1522.06   154.5 1522.72   164.2 1522.41   173.9 1521.05
   183.91518.863   193.2 1517.32   202.8 1517.39   208.91518.474   212.5 1519.11
   222.2  1522.9   231.8 1527.98   241.5 1533.36   250.7 1539.25   259.9 1545.27
   269.2 1551.05   306.1 1573.22   333.8 1590.18     343 1595.75   352.2 1601.19
#Mann= 6 ,-1 , 0
       0     .06       0   11.32     .12       0   78.63     .06       0
   87.23     .12       0   183.9    .045       0   208.9     .12       0
#XS Ineff= 2 , 0
          151.08 1526.15
Permanent Ineff=
       F       F
Bank Sta=183.9,208.9
XS Rating Curve= 0 ,0
Exp/Cntr=0.3,0.1

Type RM Length L Ch R = 1 ,15720   ,80.4,104.7,127.9
XS GIS Cut Line= 4
     1865773.901       254048.43     1865643.692       254039.75
     1865556.887      254138.708     1865534.317      254310.583
#Sta/Elev= 30
       0 1521.24    65.2 1520.57    93.2 1520.08   121.2 1519.04   130.5 1518.89
   158.7 1518.72   168.1  1517.6   177.5 1515.17   182.71514.003   186.9 1513.06
   196.3  1512.2   205.7 1513.26   207.7  1513.7   224.5 1517.43   233.9 1518.43
   243.3 1518.84   262.1 1519.42     291 1520.81   300.7 1521.89   310.3 1524.36
   319.9 1528.33   329.6 1533.39   339.2  1539.3   348.8  1546.1   368.1 1560.66
   377.7 1567.52   387.3 1573.99   406.6 1586.52   425.8 1598.92   435.5 1605.04
#Mann= 3 ,-1 , 0
       0     .12       0   182.7    .045       0   207.7     .12       0
Bank Sta=182.7,207.7
XS Rating Curve= 0 ,0
Exp/Cntr=0.3,0.1

Type RM Length L Ch R = 1 ,15615.3 ,94.7,92.7,91.8
XS GIS Cut Line= 2
     1865775.637      254029.333     1865240.915      253984.194
#Sta/Elev= 30
       0 1521.63    87.8 1520.76   107.3 1520.11   126.8 1519.03   136.6 1518.86
  163.831518.939   195.1 1519.43   204.9 1518.79   214.6 1516.62  217.991515.596
   224.4 1513.66   230.41512.497   234.2 1511.76   243.9 1511.24   253.7 1511.96
   255.41512.247   273.2 1515.51     283 1516.99   315.81519.652     322 1520.31
   331.7 1520.89   341.5 1520.46     361 1518.62   370.8 1518.05   409.8 1516.35
   419.5 1516.13  457.941515.936   479.51515.374   507.4 1514.84   536.6 1513.53
#Mann= 8 ,-1 , 0
       0     .12       0  163.83     .06       0  217.99     .12       0
   230.4    .045       0   255.4     .12       0   315.8     .06       0
  457.94     .12       0   479.5     .06       0
#XS Ineff= 2 , 0
                          333.75         1521.35
Permanent Ineff=
       F       F
Bank Sta=230.4,255.4
XS Rating Curve= 0 ,0
Exp/Cntr=0.3,0.1

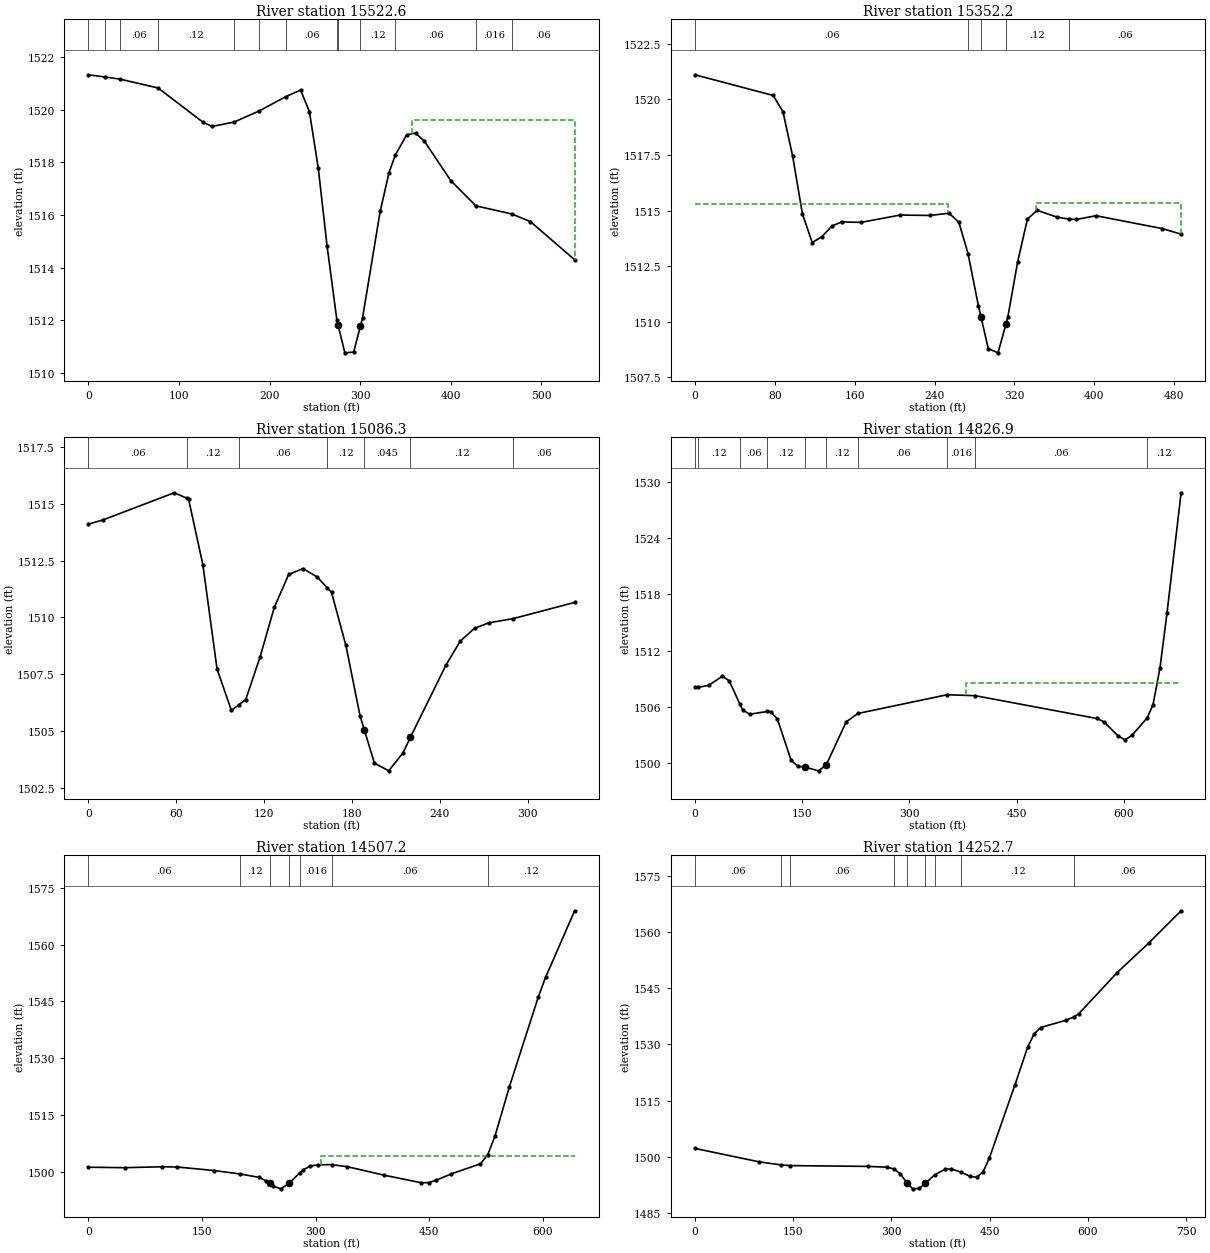
Type RM Length L Ch R = 1 ,15522.6 ,194.6,170.4,146.1
XS GIS Cut Line= 2
     1865775.637      253951.208     1865240.915      253906.069
#Sta/Elev= 30
       0 1521.32   18.311521.235   34.691521.157   76.88 1520.82   126.8 1519.51
   136.6 1519.36  160.771519.527  188.63 1519.95   218.11520.495   234.2 1520.74
   243.9 1519.92   253.7 1517.77   263.4 1514.82  274.271511.999   275.51511.825
     283 1510.77   292.7  1510.8  300.111511.775   302.5 1512.09     322 1516.14
   331.7  1517.6  338.521518.261   351.2 1519.04     361 1519.11   370.8  1518.8
     400  1517.3  427.581516.347  466.971516.041   487.8 1515.75   536.6  1514.3
#Mann= 13 ,-1 , 0
       0     .06       0   18.31     .12       0   34.69     .06       0
   76.88     .12       0  160.77     .08       0  188.63     .12       0
   218.1     .06       0  274.27     .12       0   275.5    .045       0
  300.11     .12       0  338.52     .06       0  427.58    .016       0
  466.97     .06       0
#XS Ineff= 2 , 0
                          356.66         1519.61
Permanent Ineff=
       F       F
Bank Sta=275.5,300.11
XS Rating Curve= 0 ,0
Exp/Cntr=0.3,0.1

Type RM Length L Ch R = 1 ,15352.2 ,279.3,266,252.2
XS GIS Cut Line= 3
     1865570.507      253548.885     1865331.192      253871.347
     1865246.123      253864.403
#Sta/Elev= 30
       0 1521.11    78.4 1520.18    88.2 1519.45    97.9 1517.45   107.7 1514.85
   117.5 1513.56   127.3 1513.83   137.1  1514.3   146.9 1514.49   166.5 1514.47
   205.7  1514.8   235.1 1514.78   254.6 1514.88   264.4 1514.47  273.511513.066
     284  1510.7   286.61510.194   293.8 1508.79   303.6  1508.6   311.61509.913
   313.4 1510.21   323.2 1512.69     333 1514.62   342.8 1515.01   362.4 1514.71
  374.311514.616     382  1514.6   401.6 1514.77     468 1514.19   486.9 1513.94
#Mann= 5 ,-1 , 0
       0     .06       0  273.51     .12       0   286.6    .045       0
   311.6     .12       0  374.31     .06       0
#XS Ineff= 2 , 0
          253.87 1515.28  341.59         1515.33
Permanent Ineff=
       F       F
Bank Sta=286.6,311.6
XS Rating Curve= 0 ,0
Exp/Cntr=0.3,0.1

Type RM Length L Ch R = 1 ,15086.3 ,260.2,259.4,258.6
XS GIS Cut Line= 2
     1865153.841      253501.142     1865141.956      253833.153
#Sta/Elev= 30
       0 1514.11     9.8 1514.29    58.6 1515.49   67.641515.241    68.4 1515.22
    78.2 1512.32    87.9 1507.72    97.7  1505.9  102.741506.147   107.5 1506.38
   117.3 1508.26     127 1510.44   136.8 1511.89   146.6 1512.15   156.3 1511.78
  163.331511.292   166.1  1511.1   175.9 1508.77   185.6 1505.66  188.431505.059
   195.4 1503.58   205.2 1503.24     215 1504.04     220 1504.72   244.3  1507.9
     254 1508.95   263.8 1509.52   273.6 1509.76  290.42 1509.95   332.2 1510.66
#Mann= 7 ,-1 , 0
       0     .06       0   67.64     .12       0  102.74     .06       0
  163.33     .12       0  188.43    .045       0     220     .12       0
  290.42     .06       0
Bank Sta=188.43,220
XS Rating Curve= 0 ,0
Exp/Cntr=0.3,0.1

Type RM Length L Ch R = 1 ,14826.9 ,318.9,319.8,319.8
XS GIS Cut Line= 3
     1864887.616      253516.312     1864887.616      253872.215
      1864680.75      254121.801
#Sta/Elev= 30
       0 1508.05    4.241508.059    19.2 1508.27    38.5 1509.25    48.1 1508.75
   63.121506.233    67.3 1505.61      77 1505.19  101.351505.479   105.8 1505.47
   115.4 1504.67   134.7 1500.24   144.3 1499.61  153.621499.532   173.1 1499.13
  183.761499.768   211.6 1504.36  227.881505.263  352.811507.267   392.11507.168
   562.2 1504.73     572 1504.38   591.7 1502.89   601.5 1502.44   611.3 1502.92
  632.651504.795   640.8  1506.2   650.6 1510.16   660.4 1516.03   680.1 1528.87
#Mann= 10 ,-1 , 0
       0     .06       0    4.24     .12       0   63.12     .06       0
  101.35     .12       0  153.62    .045       0  183.76     .12       0
  227.88     .06       0  352.81    .016       0   392.1     .06       0
  632.65     .12       0
#XS Ineff= 2 , 0
                          379.26         1508.48
Permanent Ineff=
       F       F
Bank Sta=153.62,183.76
XS Rating Curve= 0 ,0
Exp/Cntr=0.3,0.1

Type RM Length L Ch R = 1 ,14507.2 ,248.1,254.4,260.4
XS GIS Cut Line= 3
     1864581.626       253475.08     1864570.776      253982.892
      1864483.97      254084.889
#Sta/Elev= 30
       0  1501.3    48.8 1501.19    97.7 1501.43   117.2 1501.37     166 1500.43
  200.151499.528   224.7 1498.66   234.4 1497.74   239.21497.035   244.2  1496.3
     254 1495.61  264.651497.023  279.191499.854   283.3  1500.6     293 1501.62
   302.8 1501.93   321.1    1502   341.9 1501.44   390.7  1499.2   439.6 1497.21
   449.3 1497.26   459.1 1497.87   478.6 1499.52   517.5 1502.21  527.12 1504.59
   536.6 1509.42   555.8 1522.54     594 1546.22   603.6 1551.38   641.9  1568.9
#Mann= 7 ,-1 , 0
       0     .06       0  200.15     .12       0   239.2    .045       0
  264.65     .12       0  279.19    .016       0   321.1     .06       0
  527.12     .12       0
#XS Ineff= 2 , 0
                          307.02         1504.32
Permanent Ineff=
       F       F
Bank Sta=239.2,264.65
XS Rating Curve= 0 ,0
Exp/Cntr=0.3,0.1

Type RM Length L Ch R = 1 ,14252.7 ,125.2,122.2,119
XS GIS Cut Line= 3
     1864525.203      253357.892     1864394.995      253462.059
     1864230.064      254013.274
#Sta/Elev= 30
       0 1502.26    98.1 1498.67  131.361497.867  145.751497.675   264.3 1497.46
   293.5 1497.25  304.211496.765     313 1495.56  323.921493.046   332.5 1491.48
   342.3 1491.59   351.61492.923  366.221495.248   381.3 1496.65     391 1496.78
  405.521495.985   420.3 1494.78     430 1494.57   439.8 1495.98   449.6 1499.75
   488.6 1519.25   508.1 1529.34   517.8 1532.77   527.6 1534.48   566.6 1536.43
  579.331537.368   586.1 1538.19   644.6 1549.14   693.4 1557.12   742.1  1565.6
#Mann= 9 ,-1 , 0
       0     .06       0  131.36     .12       0  145.75     .06       0
  304.21     .12       0  323.92    .045       0   351.6     .12       0
  366.22    .016       0  405.52     .12       0  579.33     .06       0
Bank Sta=323.92,351.6
XS Rating Curve= 0 ,0
Exp/Cntr=0.3,0.1

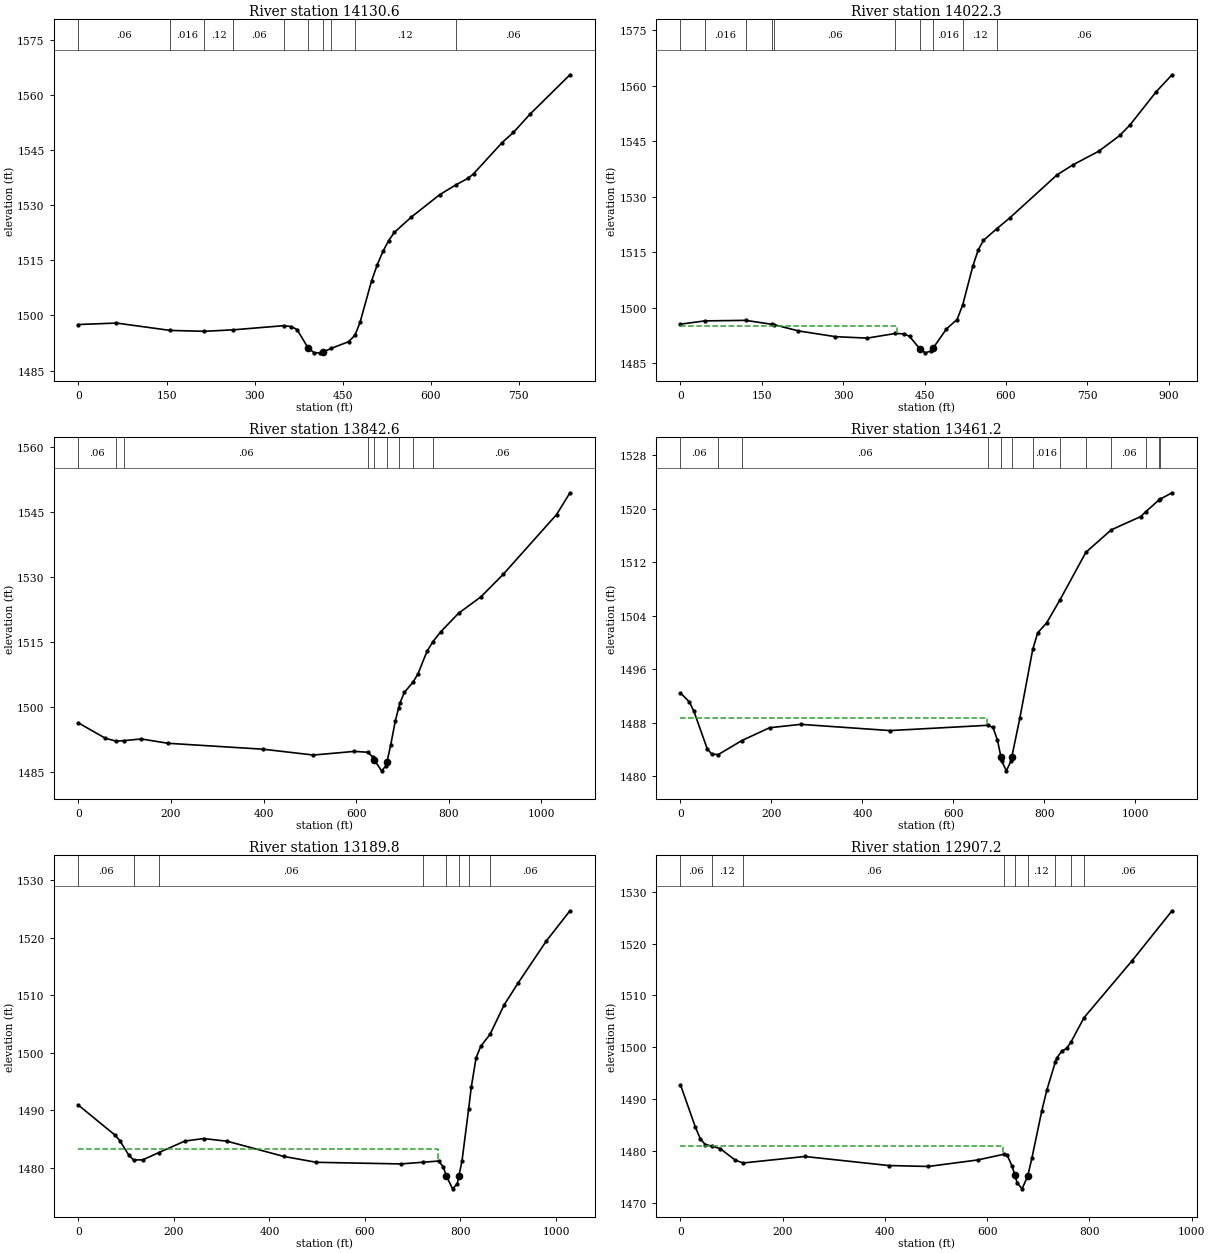
Type RM Length L Ch R = 1 ,14130.6 ,108.1,108.2,108.1
XS GIS Cut Line= 4
     1864337.869      253195.152     1864271.297       253327.51
     1864210.533      253722.476     1864193.172      254011.104
#Sta/Elev= 30
       0 1497.53    64.8 1497.92  156.331495.919  214.441495.676  263.911496.085
   349.41497.206   362.6 1496.96   372.3 1496.14   391.41491.043   401.6 1489.84
   411.3 1489.82   416.41490.057  430.581491.033     460 1492.86  470.95 1494.63
   479.5 1498.12     499 1509.35   508.8 1513.79   518.5 1517.43   528.3 1520.38
     538  1522.6     567 1526.79   615.2 1532.86  642.331535.495   663.4  1537.3
   673.1  1538.6   721.3 1547.01   740.5 1549.77   769.4 1554.84   836.9 1565.47
#Mann= 10 ,-1 , 0
       0     .06       0  156.33    .016       0  214.44     .12       0
  263.91     .06       0   349.4     .12       0   391.4    .045       0
   416.4     .12       0  430.58    .016       0  470.95     .12       0
  642.33     .06       0
Bank Sta=391.4,416.4
XS Rating Curve= 0 ,0
Exp/Cntr=0.3,0.1

Type RM Length L Ch R = 1 ,14022.3 ,181.1,179.7,178.2
XS GIS Cut Line= 4
     1864281.445      253140.899      1864162.79       253323.17
     1864102.026      253718.135     1864084.665      254006.764
#Sta/Elev= 30
       0 1495.61   44.911496.492   120.11496.639  169.421495.551   172.91495.453
   217.5 1493.78   285.7 1492.23   344.2 1491.84  396.261493.097   412.4 1492.99
   422.2 1492.32   440.9 1489.01   451.4 1487.86   461.2 1488.33   465.91489.173
   490.4 1494.34   509.9 1496.87  520.221500.767   539.1 1511.37   548.9 1515.66
   558.6 1518.27  582.851521.372   607.4 1524.37   694.2 1535.96   723.1 1538.63
   771.3 1542.37   809.9 1546.61   829.2 1549.54   877.3 1558.48   906.2 1563.01
#Mann= 10 ,-1 , 0
       0     .06       0   44.91    .016       0   120.1     .06       0
  169.42     .12       0   172.9     .06       0  396.26     .12       0
   440.9    .045       0   465.9    .016       0  520.22     .12       0
  582.85     .06       0
#XS Ineff= 2 , 0
          399.38  1495.2
Permanent Ineff=
       F       F
Bank Sta=440.9,465.9
XS Rating Curve= 0 ,0
Exp/Cntr=0.3,0.1

Type RM Length L Ch R = 1 ,13842.6 ,385.1,381.5,377.8
XS GIS Cut Line= 4
     1864166.428      252969.458     1863984.838      253130.028
     1863934.925      253687.753      1864006.54      253937.319
#Sta/Elev= 30
       0 1496.33    58.2  1492.8   81.761492.111   97.66 1492.24   135.7 1492.63
   193.9 1491.63   399.6 1490.26   507.6 1488.92     596 1489.76  624.951489.565
   635.4 1488.52  639.581487.727     655 1485.27   664.8 1486.46  666.551487.305
   674.6 1491.19   684.5 1496.73  692.041499.892   694.3 1500.84   704.1 1503.37
  723.071505.777   733.6 1507.67   753.2 1512.89  765.971515.102   782.7 1517.37
   821.6 1521.69   869.7 1525.46   917.8 1530.65  1033.1 1544.46    1062 1549.48
#Mann= 9 ,-1 , 0
       0     .06       0   81.76     .12       0   97.66     .06       0
  624.95     .12       0  639.58    .045       0  666.55     .12       0
  692.04    .016       0  723.07     .12       0  765.97     .06       0
Bank Sta=639.58,666.55
XS Rating Curve= 0 ,0
Exp/Cntr=0.3,0.1

Type RM Length L Ch R = 1 ,13461.2 ,263.1,271.4,279.5
XS GIS Cut Line= 4
     1863680.316      252860.951      1863539.96      253151.729
     1863574.682      253622.649     1863832.929      253744.177
#Sta/Elev= 30
       0 1492.43    19.6 1491.09    29.4 1489.71    58.7  1484.1    68.5 1483.31
   82.831483.209  134.751485.313   195.7 1487.23   264.2 1487.74   460.6 1486.81
  675.361487.598   686.9 1487.28   696.7 1485.39  704.41 1482.88   706.5  1482.2
   716.4 1480.79   726.2 1482.24  728.46 1482.93   745.9 1488.65  774.271498.934
   785.2 1501.42   804.9 1502.91  834.341506.373  891.231513.471  946.891516.817
  1011.6  1518.8 1022.841519.539 1052.571521.327 1054.921521.428  1080.5 1522.36
#Mann= 13 ,-1 , 0
       0     .06       0   82.83     .12       0  134.75     .06       0
  675.36     .12       0  704.41    .045       0  728.46     .12       0
  774.27    .016       0  834.34     .06       0  891.23     .12       0
  946.89     .06       0 1022.84    .016       0 1052.57     .06       0
 1054.92     .12       0
#XS Ineff= 2 , 0
          673.68  1488.7
Permanent Ineff=
       F       F
Bank Sta=704.41,728.46
XS Rating Curve= 0 ,0
Exp/Cntr=0.3,0.1

Type RM Length L Ch R = 1 ,13189.8 ,282.7,282.6,282.5
XS GIS Cut Line= 3
     1863500.195      252791.506     1863487.633      252925.547
     1863233.102      253783.239
#Sta/Elev= 30
       0 1490.87    76.9 1485.65    86.6 1484.72   105.8 1482.15  115.461481.359
   134.6 1481.36  168.231482.635   223.1 1484.64   262.4 1485.07   311.6  1484.6
   429.6 1481.97   498.4 1480.94   675.4 1480.66  721.291480.954     754 1481.16
   763.8 1480.18  770.311478.608   783.5 1476.33   793.3 1477.22  796.571478.523
   803.2 1481.16  817.031490.175   822.8 1494.09   832.7 1499.11   842.5 1501.11
  862.011503.205   891.6 1508.32   921.2 1512.17   980.1 1519.44  1029.3 1524.66
#Mann= 8 ,-1 , 0
       0     .06       0  115.46     .12       0  168.23     .06       0
  721.29     .12       0  770.31    .045       0  796.57     .12       0
  817.03    .016       0  862.01     .06       0
#XS Ineff= 2 , 0
          752.94 1483.18
Permanent Ineff=
       F       F
Bank Sta=770.31,796.57
XS Rating Curve= 0 ,0
Exp/Cntr=0.3,0.1

Type RM Length L Ch R = 1 ,12907.2 ,265,263.9,262.8
XS GIS Cut Line= 4
     1863133.441      252798.017     1863161.922      253029.767
     1863017.824      253521.087     1862998.727      253736.364
#Sta/Elev= 30
       0 1492.79    29.2  1484.6    38.9 1482.36    48.6 1481.28   60.961480.993
    77.8 1480.49     107 1478.28  122.511477.731   243.2 1478.98   407.4 1477.24
   484.7 1477.06   581.3 1478.31   632.4 1479.41   639.2 1479.19   648.9 1477.08
   654.11475.381   658.6 1473.91   668.2 1472.75   679.11475.154   687.5 1478.68
   706.9 1487.82   716.5 1491.71  733.071497.108   735.8 1497.89   745.5 1499.25
   755.3  1499.8  763.841501.016  789.591505.739     883 1516.64   961.6 1526.31
#Mann= 9 ,-1 , 0
       0     .06       0   60.96     .12       0  122.51     .06       0
   632.4     .12       0   654.1    .045       0   679.1     .12       0
  733.07    .016       0  763.84     .12       0  789.59     .06       0
#XS Ineff= 2 , 0
          630.55 1481.05
Permanent Ineff=
       F       F
Bank Sta=654.1,679.1
XS Rating Curve= 0 ,0
Exp/Cntr=0.3,0.1

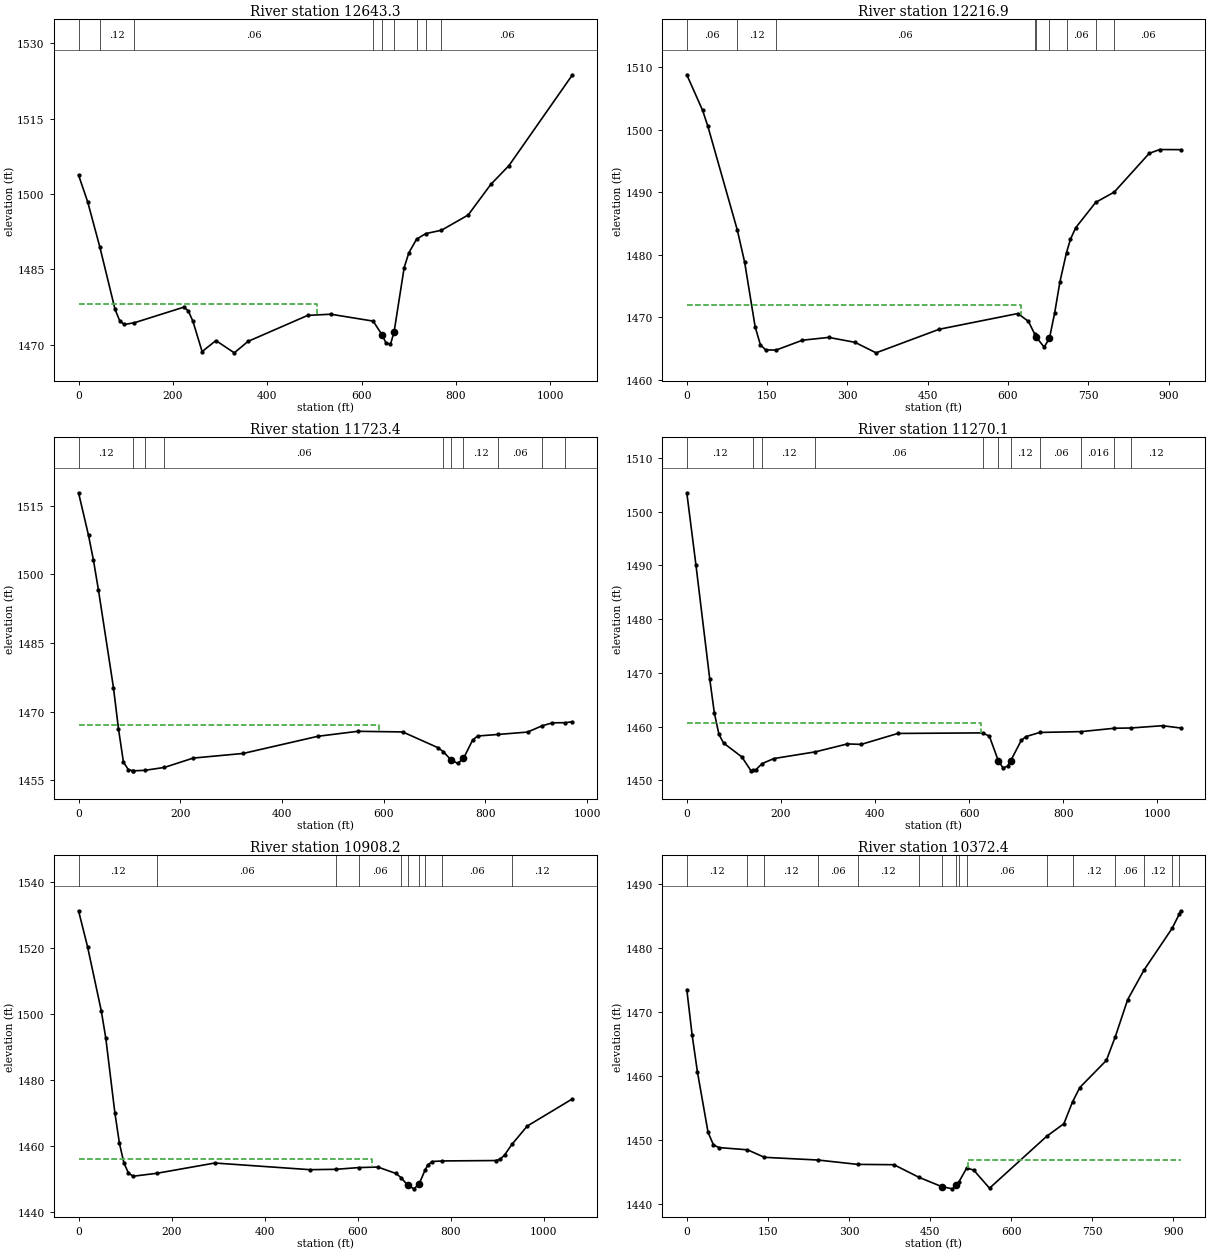
Type RM Length L Ch R = 1 ,12643.3 ,426.8,426.3,425.2
XS GIS Cut Line= 4
     1862918.598      252765.465     1862899.564      252909.338
     1862755.672      253505.462     1862955.324      253713.795
#Sta/Elev= 30
       0 1503.78    19.4 1498.43   45.251489.408    77.4 1477.05    87.1 1474.83
    96.8 1474.06  118.371474.405     223  1477.5   232.7 1476.77   242.5 1474.67
   261.9 1468.67   291.1 1470.86   330.1 1468.42   359.3  1470.7   485.8 1475.87
   534.5  1476.1  624.391474.732  643.431471.992   651.3 1470.45     661 1470.08
   668.81472.578   690.2 1485.38     700  1488.3  716.621491.045  736.091492.137
  769.231492.805   825.7 1495.82   873.8 1501.92   912.3 1505.66  1046.9 1523.72
#Mann= 9 ,-1 , 0
       0     .06       0   45.25     .12       0  118.37     .06       0
  624.39     .12       0  643.43    .045       0   668.8     .12       0
  716.62    .016       0  736.09     .12       0  769.23     .06       0
#XS Ineff= 2 , 0
          505.26 1478.09
Permanent Ineff=
       F       F
Bank Sta=643.43,668.8
XS Rating Curve= 0 ,0
Exp/Cntr=0.3,0.1

Type RM Length L Ch R = 1 ,12216.9 ,484.1,493.6,502.9
XS GIS Cut Line= 3
     1862621.289      252704.701     1862395.429       253162.58
     1862312.963      253566.226
#Sta/Elev= 30
       0 1508.79    29.5  1503.1    39.3 1500.56   94.511483.896     108 1478.82
   127.6 1468.49   137.5 1465.57   147.3 1464.78  166.641464.739     216 1466.32
   265.1 1466.77   314.2 1465.98   353.5  1464.3   471.3 1468.07   618.4 1470.59
   638.1 1469.33  649.771467.299   652.71466.797   667.5 1465.22  677.391466.648
   687.1  1470.7   696.9 1475.67   709.2 1480.35   716.6 1482.48   726.4 1484.32
  763.751488.379  798.411490.024   863.7 1496.22   883.3 1496.83   922.5 1496.81
#Mann= 9 ,-1 , 0
       0     .06       0   94.51     .12       0  166.64     .06       0
  649.77     .12       0   652.7    .045       0  677.39     .12       0
   709.2     .06       0  763.75    .016       0  798.41     .06       0
#XS Ineff= 2 , 0
          623.32 1471.91
Permanent Ineff=
       F       F
Bank Sta=652.7,677.39
XS Rating Curve= 0 ,0
Exp/Cntr=0.3,0.1

Type RM Length L Ch R = 1 ,11723.4 ,466.5,453.2,439.7
XS GIS Cut Line= 3
      1862104.63       252537.58     1861970.081      253110.496
     1861748.727      253422.996
#Sta/Elev= 30
       0 1517.82    19.6 1508.51    29.4 1503.03    39.2 1496.53    68.7 1475.22
    78.5 1466.27    88.3 1458.96    98.1  1457.3  107.581457.068   107.9 1457.06
  130.21 1457.17  168.661457.802   225.6 1459.85   323.7 1460.86   470.8 1464.61
   549.3  1465.7   637.6 1465.56   706.3 1462.15  717.561461.248   732.11459.489
   745.6  1458.7   757.1 1459.76   775.1 1463.78   784.9 1464.67  825.451465.014
   883.1 1465.53  912.061466.915   932.2 1467.55  957.781467.582   971.5  1467.8
#Mann= 10 ,-1 , 0
       0     .12       0  107.58     .08       0  130.21     .12       0
  168.66     .06       0  717.56     .12       0   732.1    .045       0
   757.1     .12       0  825.45     .06       0  912.06    .016       0
  957.78     .06       0
#XS Ineff= 2 , 0
          591.33 1467.03
Permanent Ineff=
       F       F
Bank Sta=732.1,757.1
XS Rating Curve= 0 ,0
Exp/Cntr=0.3,0.1

Type RM Length L Ch R = 1 ,11270.1 ,350.9,361.9,371.6
XS GIS Cut Line= 3
     1861709.665      252407.371      1861488.31      252906.503
      1861475.29      253409.976
#Sta/Elev= 30
       0 1503.53    19.5 1490.04    48.8 1468.84    58.5 1462.58    68.2  1458.6
      78 1456.96     117 1454.37   136.5 1451.78  140.531451.846   146.2 1451.94
  160.111453.129   185.2 1454.07  273.421455.317   341.3 1456.79   370.5  1456.7
   448.5 1458.74  628.521458.841   642.9 1458.24  661.941453.667   671.9 1452.33
   681.6 1452.65  688.551453.703   710.7 1457.44   720.4 1458.14  749.911458.924
   838.3 1459.08  908.851459.708  943.421459.752  1010.9 1460.18  1049.6 1459.75
#Mann= 11 ,-1 , 0
       0     .12       0  140.53     .08       0  160.11     .12       0
  273.42     .06       0  628.52     .12       0  661.94    .045       0
  688.55     .12       0  749.91     .06       0   838.3    .016       0
  908.85     .06       0  943.42     .12       0
#XS Ineff= 2 , 0
          625.39 1460.64
Permanent Ineff=
       F       F
Bank Sta=661.94,688.55
XS Rating Curve= 0 ,0
Exp/Cntr=0.3,0.1

Type RM Length L Ch R = 1 ,10908.2 ,526.6,535.8,545
XS GIS Cut Line= 3
     1861301.679      252298.864     1861301.679      252650.427
     1860971.817      253279.767
#Sta/Elev= 30
       0 1531.27    19.5 1520.28    48.8 1500.98    58.6 1492.63    78.1 1470.01
    87.9 1460.74    97.7 1454.72   107.4 1451.73   117.2 1450.77  168.571451.669
     293 1454.78   497.6 1452.76  553.531452.872  602.911453.399   643.6 1453.56
   682.5 1451.61  693.621450.344   707.51448.071   721.4 1446.95   732.5 1448.49
  744.811452.536   750.6 1454.13   760.4 1455.24  782.09 1455.41   896.6 1455.53
   906.4 1455.89   916.1 1457.22  932.081460.464   964.8 1465.98  1062.1 1474.24
#Mann= 10 ,-1 , 0
       0     .12       0  168.57     .06       0  553.53    .016       0
  602.91     .06       0  693.62     .12       0   707.5    .045       0
   732.5     .12       0  744.81    .016       0  782.09     .06       0
  932.08     .12       0
#XS Ineff= 2 , 0
          630.34 1456.05
Permanent Ineff=
       F       F
Bank Sta=707.5,732.5
XS Rating Curve= 0 ,0
Exp/Cntr=0.3,0.1

Type RM Length L Ch R = 1 ,10372.4 ,602.8,607.7,611.8
XS GIS Cut Line= 2
     1861123.727      252320.566     1860411.922      252893.483
#Sta/Elev= 30
       0 1473.45     9.8  1466.4    19.6 1460.63    39.3 1451.17    49.1 1449.23
      59 1448.78  112.251448.428  143.521447.255  242.641446.831  315.971446.151
   383.2  1446.1  429.441444.132  471.191442.692   491.2 1442.33  498.89 1442.86
  503.761443.474  517.711445.568   530.6 1445.27     560 1442.43  665.621450.531
   697.6 1452.51  713.59 1455.92     727 1458.16   776.2  1462.4   792.81466.125
   815.5 1471.88  845.851476.515  897.741483.023  911.191485.276   913.7 1485.77
#Mann= 16 ,-1 , 0
       0     .12       0  112.25    .016       0  143.52     .12       0
  242.64     .06       0  315.97     .12       0  429.44     .06       0
  471.19    .045       0  498.89     .06       0  503.76     .12       0
  517.71     .06       0  665.62    .016       0  713.59     .12       0
   792.8     .06       0  845.85     .12       0  897.74     .06       0
  911.19     .12       0
#XS Ineff= 2 , 0
                          520.12         1446.84
Permanent Ineff=
       F       F
Bank Sta=471.19,498.89
XS Rating Curve= 0 ,0
Exp/Cntr=0.3,0.1