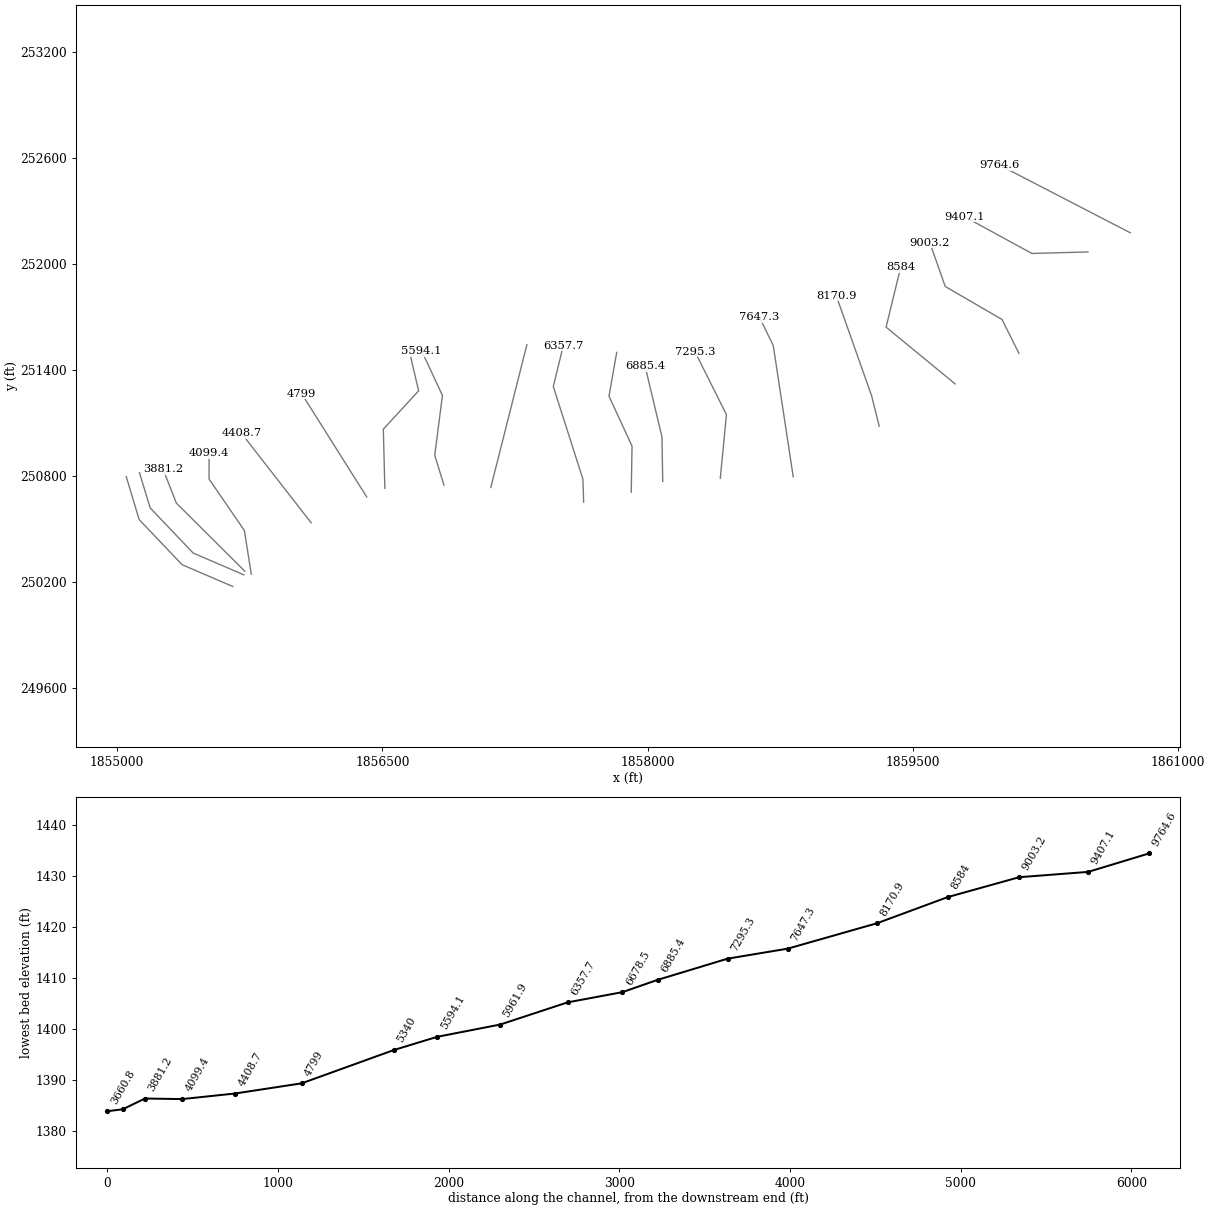
HEC-RAS study BUSHYFK.prj: BUSHYFK

--- BUSHYFK.g01 (geometry) --- (continued)

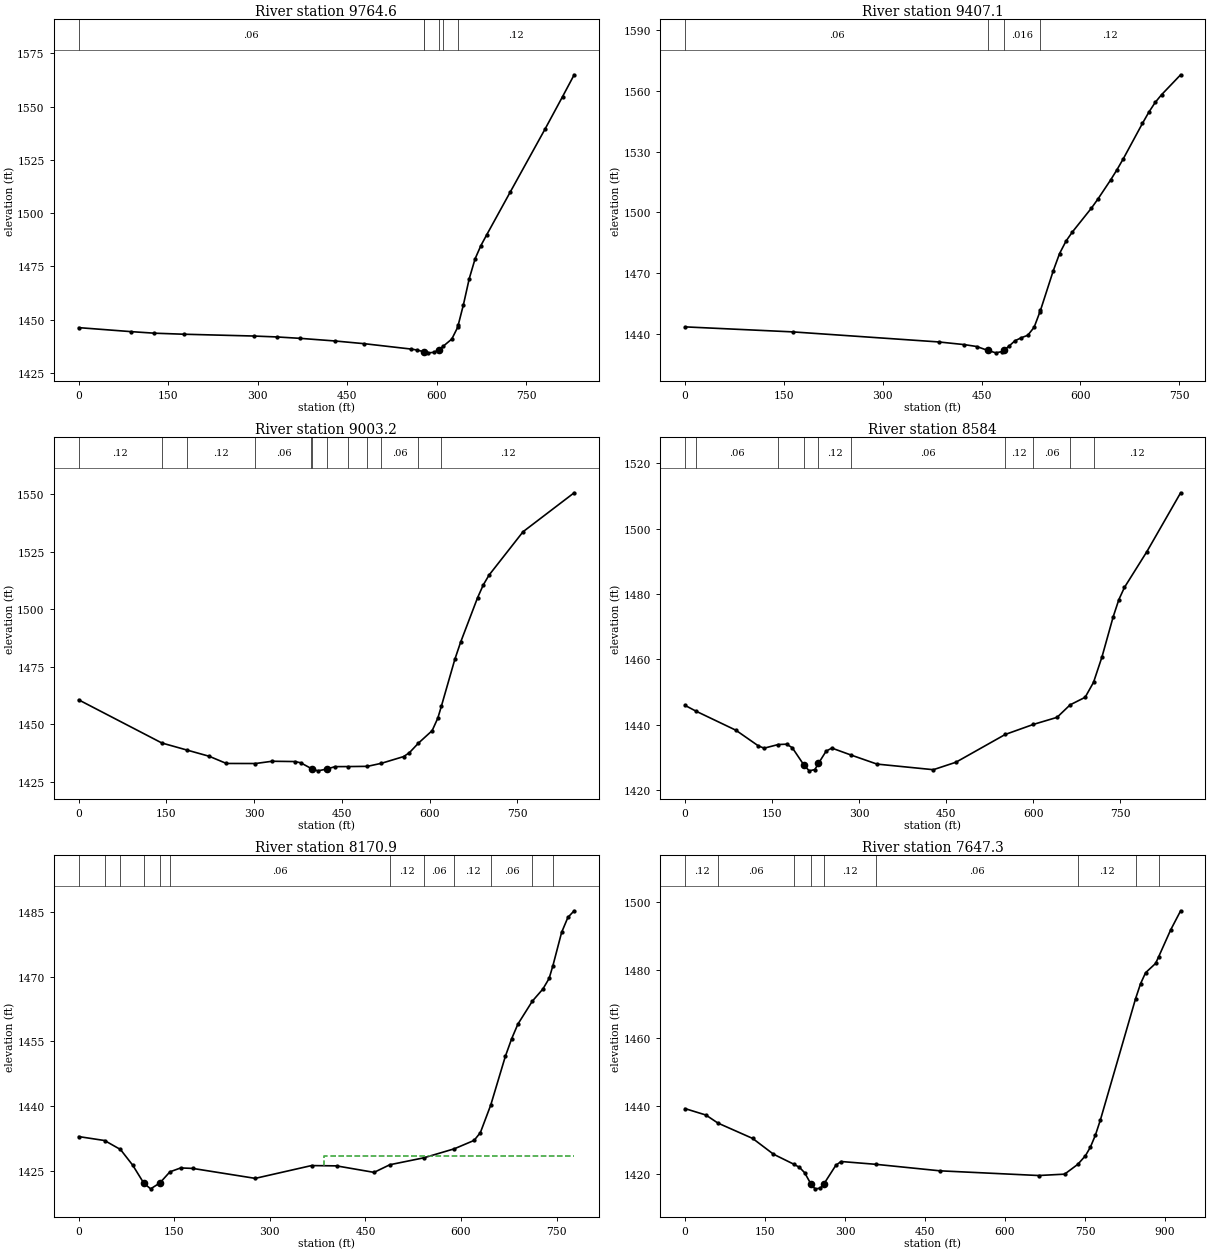
Type RM Length L Ch R = 1 ,9764.6  ,358,357.5,357
XS GIS Cut Line= 2
     1860728.762      252177.337     1859990.915      252559.281
#Sta/Elev= 30
       0 1446.25      88 1444.37   127.1 1443.64   175.9 1443.16   293.2 1442.31
   332.3 1441.88   371.4 1441.22   430.1 1439.98     479 1438.71   557.2  1436.2
   566.9 1435.77  578.611434.935   578.71434.929   586.5 1434.42   596.2 1434.67
   603.71435.932     606 1436.32  611.591437.609   625.6 1440.88   635.4 1446.36
  636.23 1447.27   645.1 1456.99   654.9 1469.26   664.7 1478.56   674.4 1484.75
   684.2 1489.83   723.3 1509.73     782 1539.46   811.3 1554.65   830.8 1564.92
#Mann= 6 ,-1 , 0
       0     .06       0  578.61     .12       0   578.7    .045       0
   603.7     .12       0  611.59    .016       0  636.23     .12       0
Bank Sta=578.7,603.7
XS Rating Curve= 0 ,0
Exp/Cntr=0.3,0.1

Type RM Length L Ch R = 1 ,9407.1  ,404.5,403.9,403.3
XS GIS Cut Line= 3
     1860490.047       252068.83     1860173.206      252060.149
     1859791.262      252268.483
#Sta/Elev= 30
       0  1443.6   163.3 1441.13   384.6 1436.18   423.3 1434.87   442.6 1433.92
   459.21431.998   471.6  1430.8   481.3 1431.46   484.21432.204     491 1433.95
   500.6 1436.75   510.3 1438.26     520 1439.45   529.7 1443.42  538.191450.787
   539.3 1451.75   558.7 1471.27   568.3 1479.77     578 1485.86   587.7 1490.38
   616.7 1502.18   626.3 1506.54   645.7 1515.99   655.4 1521.07     665 1526.49
     694 1543.89   703.7 1549.42   713.4 1554.26     723 1558.04     752 1567.88
#Mann= 4 ,-1 , 0
       0     .06       0   459.2    .045       0   484.2    .016       0
  538.19     .12       0
Bank Sta=459.2,484.2
XS Rating Curve= 0 ,0
Exp/Cntr=0.3,0.1

Type RM Length L Ch R = 1 ,9003.2  ,422.8,419.2,415.6
XS GIS Cut Line= 4
     1860099.422      251495.913     1860003.935      251686.885
     1859682.755      251873.517     1859595.949      252120.913
#Sta/Elev= 30
       0 1460.66  142.251441.877  185.041438.816   223.3 1436.09   252.6 1432.97
  302.341432.945   330.8 1433.93   369.9  1433.8   379.7 1433.26  397.941430.734
     3991430.571     409 1429.76     4241430.517   438.4 1431.59  459.931431.618
  493.771431.717  517.571433.036   555.6 1435.96   565.4 1437.63  580.97 1441.82
   604.4 1447.25   614.1 1452.71  620.041457.768   643.2 1478.29     653 1485.69
   682.1 1505.12   691.8 1510.64   701.5 1514.87   759.8 1533.79   847.2 1550.74
#Mann= 12 ,-1 , 0
       0     .12       0  142.25     .06       0  185.04     .12       0
  302.34     .06       0  397.94     .12       0     399    .045       0
     424     .12       0  459.93     .06       0  493.77     .12       0
  517.57     .06       0  580.97    .016       0  620.04     .12       0
Bank Sta=399,424
XS Rating Curve= 0 ,0
Exp/Cntr=0.3,0.1

Type RM Length L Ch R = 1 ,8584    ,427.4,413.1,398.4
XS GIS Cut Line= 3
     1859739.179      251322.302     1859348.554      251643.483
     1859431.019      251982.024
#Sta/Elev= 30
       0 1445.89   19.451444.076    87.5  1438.3   126.4 1433.49   136.2  1432.8
  160.721433.921     175 1434.02   184.8 1432.93  205.061427.575     214 1425.86
   223.7 1426.26  229.811428.117   243.1 1431.89   252.9 1432.83  285.531430.731
   330.7 1427.93   427.9 1426.21   466.8 1428.49  551.931437.007  600.531440.085
   641.2 1442.24  663.691446.064   689.6 1448.38  704.041452.961   718.6 1460.74
     738 1473.07   747.7 1478.29   757.4 1482.04   796.1 1493.01   854.2    1511
#Mann= 10 ,-1 , 0
       0     .12       0   19.45     .06       0  160.72     .12       0
  205.06    .045       0  229.81     .12       0  285.53     .06       0
  551.93     .12       0  600.53     .06       0  663.69    .016       0
  704.04     .12       0
Bank Sta=205.06,229.81
XS Rating Curve= 0 ,0
Exp/Cntr=0.3,0.1

Type RM Length L Ch R = 1 ,8170.9  ,525.6,523.7,521.5
XS GIS Cut Line= 3
     1859309.491      251083.587     1859266.088      251257.198
     1859066.435      251821.434
#Sta/Elev= 30
       0 1432.88   40.721431.962   65.631429.882    84.8 1426.25  102.34 1422.04
     113 1420.75   127.41422.108  143.241424.698   160.1  1425.6     179 1425.49
   277.1 1423.18   365.4 1426.15   404.6 1426.08   463.5 1424.57  488.231426.341
   541.6 1427.95  589.311430.036   620.5 1431.99   630.3 1433.79  646.59 1440.19
   669.5 1451.49   679.4 1455.58   689.2 1458.98  711.911464.315   728.4 1467.12
   738.2 1469.58  744.161472.554   757.8 1480.27   767.7 1483.76   777.5 1485.28
#Mann= 12 ,-1 , 0
       0     .12       0   40.72     .06       0   65.63     .12       0
  102.34    .045       0   127.4     .12       0  143.24     .06       0
  488.23     .12       0   541.6     .06       0  589.31     .12       0
  646.59     .06       0  711.91    .016       0  744.16     .12       0
#XS Ineff= 2 , 0
                          384.73         1428.28
Permanent Ineff=
       F       F
Bank Sta=102.34,127.4
XS Rating Curve= 0 ,0
Exp/Cntr=0.3,0.1

Type RM Length L Ch R = 1 ,7647.3  ,357.4,351.9,346.3
XS GIS Cut Line= 3
      1858823.38      250797.128     1858710.533      251539.316
     1858632.408      251699.906
#Sta/Elev= 30
       0 1439.31      39 1437.43   61.581435.067   126.7 1430.56   165.7 1425.94
  203.621423.016   214.5 1422.08   224.2  1420.5  236.17 1417.13   243.7 1415.77
   253.5 1415.95  260.641417.297   282.7 1422.68   292.5 1423.79  357.581422.968
   477.7 1421.06     663 1419.68   711.7 1420.08  736.321422.944   750.7 1425.47
   760.1 1428.02   769.5 1431.55   778.9 1436.04  844.841471.606   854.1 1475.96
   863.5 1479.18   882.3 1481.92  888.061483.869   910.5 1491.73   929.3 1497.37
#Mann= 9 ,-1 , 0
       0     .12       0   61.58     .06       0  203.62     .12       0
  236.17    .045       0  260.64     .12       0  357.58     .06       0
  736.32     .12       0  844.84    .016       0  888.06     .12       0
Bank Sta=236.17,260.64
XS Rating Curve= 0 ,0
Exp/Cntr=0.3,0.1

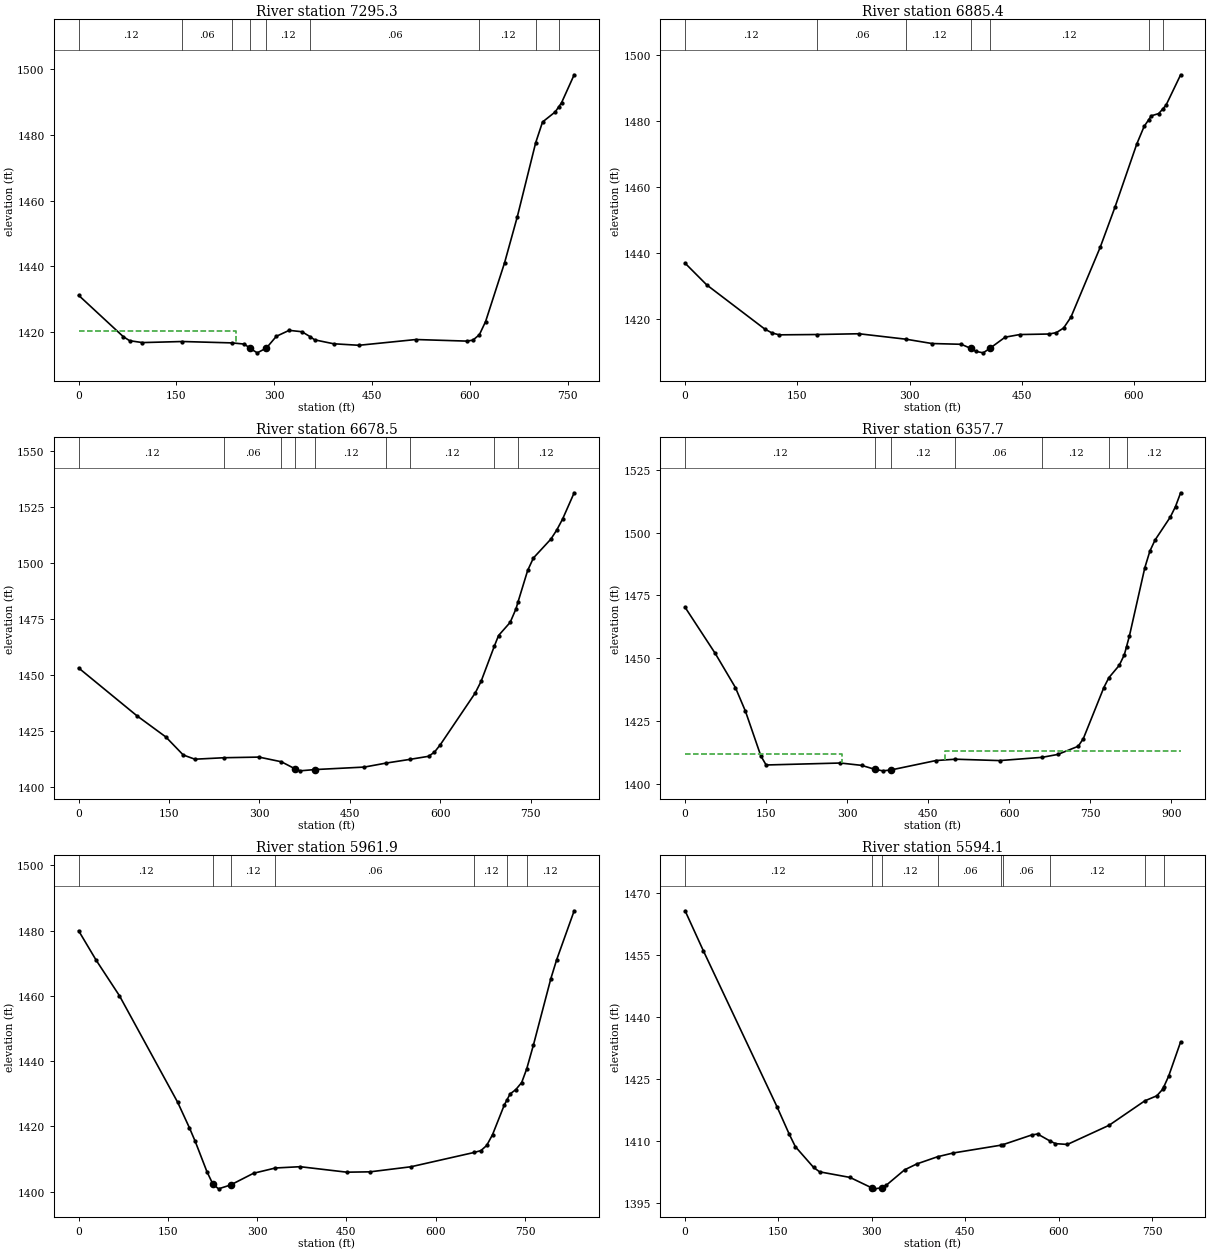
Type RM Length L Ch R = 1 ,7295.3  ,402.5,410,417.5
XS GIS Cut Line= 3
     1858411.054      250788.448     1858445.776      251148.691
     1858267.824      251504.594
#Sta/Elev= 30
       0 1431.26    68.5 1418.71    78.2 1417.49    97.8 1416.92   159.21417.245
  235.391416.822   254.3 1416.46   262.91415.144   273.9 1413.81   287.91415.266
   303.2 1418.83   322.8 1420.63   342.4 1420.21  354.951418.714   361.9 1417.75
     391 1416.56   429.8  1416.1   517.2 1417.85   594.8 1417.37   604.5 1417.65
  614.431419.296     624 1423.31   653.1 1441.13   672.5    1455  700.831477.568
   711.3 1483.82   730.7 1486.87  736.471488.518   740.4 1489.64   759.8 1498.14
#Mann= 9 ,-1 , 0
       0     .12       0   159.2     .06       0  235.39     .12       0
   262.9    .045       0   287.9     .12       0  354.95     .06       0
  614.43     .12       0  700.83    .016       0  736.47     .12       0
#XS Ineff= 2 , 0
           241.9 1420.44
Permanent Ineff=
       F       F
Bank Sta=262.9,287.9
XS Rating Curve= 0 ,0
Exp/Cntr=0.3,0.1

Type RM Length L Ch R = 1 ,6885.4  ,202.2,206.9,211.2
XS GIS Cut Line= 3
     1858085.533      250771.087     1858081.192      251022.823
     1857985.706      251422.128
#Sta/Elev= 30
       0 1436.81      29 1430.22   106.5 1416.86   116.2 1415.68   125.9 1415.11
  176.95 1415.21   232.4 1415.44   295.2 1413.79     330 1412.48   369.1 1412.25
   382.11410.979   388.6 1410.11   398.4 1409.66   407.11410.982   427.7  1414.4
   447.3  1415.2   486.4 1415.36   496.2 1415.78   505.9 1417.18   515.7 1420.48
   554.8 1441.63   574.4 1453.69   603.7 1472.92   613.5 1478.23   619.81480.321
   623.2 1481.45     633 1482.12  638.861483.645   642.8 1484.67   662.3 1493.87
#Mann= 7 ,-1 , 0
       0     .12       0  176.95     .06       0   295.2     .12       0
   382.1    .045       0   407.1     .12       0   619.8    .016       0
  638.86     .12       0
Bank Sta=382.1,407.1
XS Rating Curve= 0 ,0
Exp/Cntr=0.3,0.1

Type RM Length L Ch R = 1 ,6678.5  ,322.8,320.7,317.5
XS GIS Cut Line= 4
     1857907.581      250710.323     1857911.922      250970.739
     1857781.713      251252.858     1857825.116      251500.253
#Sta/Elev= 30
       0 1453.21    96.5  1431.9   144.7 1422.39   173.6 1414.33   192.9 1412.45
  241.771413.112   299.3 1413.39  336.47  1411.3  358.251408.267   367.3 1407.25
   391.71407.811   474.1 1408.93  510.611410.734  549.811412.377   580.8 1413.75
   590.5 1415.62   600.2 1418.93   658.1 1442.03   667.8  1447.2  690.061463.128
   696.8  1467.7   716.1 1473.58   725.7  1479.6  728.971482.563   745.1 1496.77
   754.7 1502.36   783.7  1510.8   793.4 1514.84     803 1519.69   822.3 1531.48
#Mann= 9 ,-1 , 0
       0     .12       0  241.77     .06       0  336.47     .12       0
  358.25    .045       0   391.7     .12       0  510.61     .06       0
  549.81     .12       0  690.06    .016       0  728.97     .12       0
Bank Sta=358.25,391.7
XS Rating Curve= 0 ,0
Exp/Cntr=0.3,0.1

Type RM Length L Ch R = 1 ,6357.7  ,408.3,395.8,383.2
XS GIS Cut Line= 4
     1857638.484      250653.899     1857634.144      250784.108
     1857466.655      251307.823     1857523.078      251537.858
#Sta/Elev= 30
       0 1470.29    55.8 1451.94    93.1 1438.38   111.7 1428.95   140.1 1411.23
   149.9 1407.58   287.4 1408.36   326.6 1407.43   351.11405.853   365.9 1405.25
   380.8 1405.59   464.1 1409.34  500.051409.874   581.9 1409.33  660.591410.622
   689.6 1411.77   727.5 1415.03     737  1418.1   774.9 1438.39  784.131442.288
   803.3 1447.19   812.8 1451.42  816.861454.651   822.2  1458.9   850.7 1486.05
   860.1 1492.67   869.6 1497.05     898 1506.24   907.5  1510.4     917 1515.86
#Mann= 7 ,-1 , 0
       0     .12       0   351.1    .045       0   380.8     .12       0
  500.05     .06       0  660.59     .12       0  784.13    .016       0
  816.86     .12       0
#XS Ineff= 2 , 0
          289.99 1411.96  480.91         1412.97
Permanent Ineff=
       F       F
Bank Sta=351.1,380.8
XS Rating Curve= 0 ,0
Exp/Cntr=0.3,0.1

Type RM Length L Ch R = 1 ,5961.9  ,365.1,367.8,370.5
XS GIS Cut Line= 2
      1857113.31      250736.364     1857317.304      251543.656
#Sta/Elev= 30
       0 1479.93    29.4 1470.93    68.6 1460.03   166.5 1427.38   186.1 1419.62
   195.9 1415.44   215.5  1406.2  225.531402.364   235.1  1400.9  255.381402.088
   293.9 1405.67  330.751407.286   372.2 1407.68   450.6    1406   489.8 1406.11
   558.4 1407.66  664.461412.035   675.9  1412.6   685.7 1414.18   695.5 1417.49
   715.1 1426.49  719.63 1428.08   724.9 1429.93   734.7 1431.31   744.5 1433.46
  752.891437.604   764.1 1444.86   793.5 1465.27   803.3 1471.07   832.7 1486.05
#Mann= 7 ,-1 , 0
       0     .12       0  225.53    .045       0  255.38     .12       0
  330.75     .06       0  664.46     .12       0  719.63    .016       0
  752.89     .12       0
Bank Sta=225.53,255.38
XS Rating Curve= 0 ,0
Exp/Cntr=0.3,0.1

Type RM Length L Ch R = 1 ,5594.1  ,268,254.2,240.1
XS GIS Cut Line= 4
     1856848.554      250749.385      1856796.47      250918.656
     1856839.873      251257.198     1856722.685      251508.934
#Sta/Elev= 30
       0  1465.7    29.5 1455.98   147.6 1418.36   167.3 1411.72   177.1 1408.71
   206.4 1403.69   216.1 1402.62   264.9 1401.27  299.881398.746   303.9 1398.51
  315.651398.753   323.4 1399.41   352.6  1403.1   372.1 1404.52  405.531406.263
   430.6 1407.17  507.921409.074  509.951409.151   556.7 1411.52   566.3 1411.76
   585.61410.125     595 1409.43   614.2 1409.24   681.2 1413.87  738.511419.772
   757.8 1420.99   767.4  1422.6  768.75 1423.05   776.9 1425.77   796.1 1434.03
#Mann= 9 ,-1 , 0
       0     .12       0  299.88    .045       0  315.65     .12       0
  405.53     .06       0  507.92     .12       0  509.95     .06       0
   585.6     .12       0  738.51    .016       0  768.75     .12       0
Bank Sta=299.88,315.65
XS Rating Curve= 0 ,0
Exp/Cntr=0.3,0.1

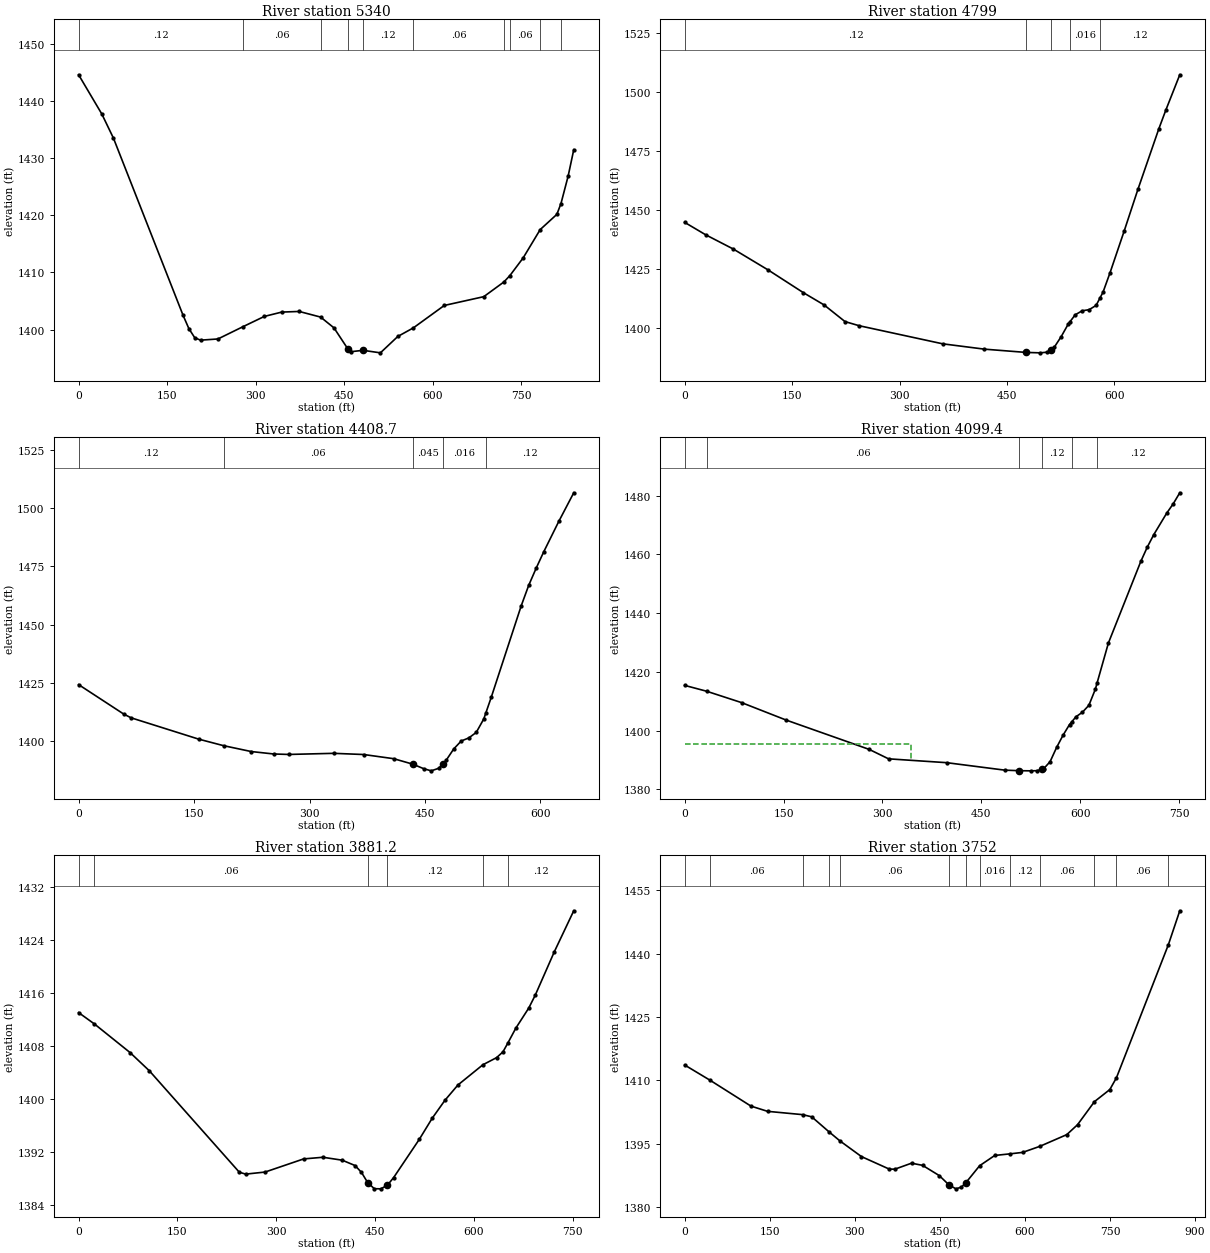
Type RM Length L Ch R = 1 ,5340    ,510.7,541,569.8
XS GIS Cut Line= 4
     1856514.352      250732.024     1856505.672      251066.226
     1856705.324      251283.239     1856657.581      251487.233
#Sta/Elev= 30
       0 1444.63    39.3 1437.76      59 1433.53     177 1402.48   186.8 1400.16
   196.7 1398.57   206.5 1398.14     236 1398.35  277.971400.478   314.6  1402.3
   344.1 1403.06   373.6 1403.17  409.911402.184   432.6 1400.29  455.921396.628
   462.1 1396.13   481.8 1396.36   511.2 1395.92   540.7 1398.79  567.221400.307
   619.4 1404.22   686.3 1405.76  720.361408.333  730.551409.455     753 1412.55
  781.881417.514   810.1 1420.18  817.071422.075   829.2 1426.88   838.7  1431.5
#Mann= 10 ,-1 , 0
       0     .12       0  277.97     .06       0  409.91     .12       0
  455.92    .045       0   481.8     .12       0  567.22     .06       0
  720.36     .12       0  730.55     .06       0  781.88    .016       0
  817.07     .12       0
Bank Sta=455.92,481.8
XS Rating Curve= 0 ,0
Exp/Cntr=0.3,0.1

Type RM Length L Ch R = 1 ,4799    ,388,390.3,392.5
XS GIS Cut Line= 2
     1856412.063      250682.619     1856043.725      251267.541
#Sta/Elev= 30
       0 1444.78    29.2 1439.53    68.2 1433.41   116.8 1424.53   165.5 1414.98
   194.7 1409.72   223.9 1402.65   243.4 1400.92   360.2 1393.22   418.6 1390.95
     477 1389.56   496.5 1389.39   506.3 1389.68  511.121390.724     516 1391.78
   525.7 1396.29   535.5  1401.6  538.171402.682   545.2 1405.53   554.9 1407.23
   564.7 1407.72   574.4 1409.52  579.941412.747   584.1 1415.17   593.9 1423.43
   613.4 1440.92   632.8  1458.8     662 1484.52   671.8 1492.48   691.2 1507.42
#Mann= 5 ,-1 , 0
       0     .12       0     477    .045       0  511.12     .12       0
  538.17    .016       0  579.94     .12       0
Bank Sta=477,511.12
XS Rating Curve= 0 ,0
Exp/Cntr=0.3,0.1

Type RM Length L Ch R = 1 ,4408.7  ,310.6,309.3,308
XS GIS Cut Line= 2
     1856097.685      250536.712      1855702.72      251044.524
#Sta/Elev= 30
       0 1424.33    58.5 1411.74    68.2 1410.11     156 1400.98   188.41398.175
   224.2 1395.67   253.4 1394.62   272.9 1394.42   331.4  1394.9   370.4 1394.39
   409.4  1392.6  434.151390.263   448.4 1388.32   458.1  1387.4   467.9  1388.5
  473.041390.335   477.6 1391.96   487.4 1396.79   497.1 1400.18   506.9 1401.49
   516.6 1403.85   526.4 1409.62  528.911412.019   536.1 1418.89   575.1 1458.14
   584.8 1466.87   594.6  1474.3   604.3 1481.21   623.8  1494.2   643.3  1506.5
#Mann= 5 ,-1 , 0
       0     .12       0   188.4     .06       0  434.15    .045       0
  473.04    .016       0  528.91     .12       0
Bank Sta=434.15,473.04
XS Rating Curve= 0 ,0
Exp/Cntr=0.3,0.1

Type RM Length L Ch R = 1 ,4099.4  ,214,218.2,222.3
XS GIS Cut Line= 4
     1855759.144      250245.913     1855720.081      250493.309
     1855520.429      250784.108     1855520.429      250931.677
#Sta/Elev= 30
       0 1415.42   33.261413.429    86.7 1409.52   154.1 1403.59   279.9 1393.61
   309.2  1390.4   397.4 1389.09   485.6 1386.54   507.51386.358   524.8 1386.31
   534.6 1386.36   542.11386.873   544.5 1387.05   554.2 1389.45     564 1394.26
   573.8 1398.44   583.6 1402.07  587.451403.115   593.4 1404.73   603.2 1406.28
     613 1408.64   622.9 1414.18  625.321416.168   642.6 1429.86   691.7 1457.63
   701.6 1462.54   711.4 1466.77   731.1 1474.12   740.9 1477.27   750.8 1481.02
#Mann= 6 ,-1 , 0
       0     .12       0   33.26     .06       0   507.5    .045       0
   542.1     .12       0  587.45    .016       0  625.32     .12       0
#XS Ineff= 2 , 0
          343.45 1395.41
Permanent Ineff=
       F       F
Bank Sta=507.5,542.1
XS Rating Curve= 0 ,0
Exp/Cntr=0.3,0.1

Type RM Length L Ch R = 1 ,3881.2  ,129.8,129.3,128.7
XS GIS Cut Line= 3
     1855722.178      250263.442     1855335.025      250648.859
     1855260.372      250839.831
#Sta/Elev= 30
       0 1412.99   24.081411.269      78 1406.97   107.3 1404.22   243.9 1388.92
   253.6 1388.64   282.9 1388.95   341.4 1390.93   370.7 1391.18     400 1390.74
   419.5 1389.93   429.2  1388.9   438.61387.365   448.7 1386.44   458.5 1386.42
   468.61386.969     478 1388.12     517 1393.89   536.5 1397.06     556 1399.79
   575.6 1402.08   613.41405.123   634.2  1406.2   643.9 1407.07  651.711408.473
   663.5 1410.66     683 1413.67   692.8  1415.6     722  1422.2   751.3 1428.34
#Mann= 6 ,-1 , 0
       0     .12       0   24.08     .06       0   438.6    .045       0
   468.6     .12       0   613.4    .016       0  651.71     .12       0
Bank Sta=438.6,468.6
XS Rating Curve= 0 ,0
Exp/Cntr=0.3,0.1

Type RM Length L Ch R = 1 ,3752    ,91.2,91.1,91.2
XS GIS Cut Line= 4
     1855716.969      250242.609     1855430.511      250365.873
     1855187.455      250621.081     1855126.692      250820.734
#Sta/Elev= 30
       0 1413.63   44.871410.014   116.9  1403.9   146.2 1402.66  208.171401.876
   224.1 1401.36  254.321397.839  273.861395.659   311.8 1391.95   360.8 1388.99
   370.6 1388.97     400 1390.39   419.5 1389.88   448.9 1387.46   465.8 1385.29
   478.3 1384.32   488.1 1384.74   495.81385.762   520.11389.788   546.8 1392.22
  572.791392.586   595.8 1392.94  626.231394.374   673.8 1397.15   692.7 1399.49
  722.571404.956   749.7 1407.82  761.371410.609  852.771442.041     873 1450.12
#Mann= 13 ,-1 , 0
       0     .12       0   44.87     .06       0  208.17     .12       0
  254.32    .016       0  273.86     .06       0   465.8    .045       0
   495.8     .12       0   520.1    .016       0  572.79     .12       0
  626.23     .06       0  722.57    .016       0  761.37     .06       0
  852.77     .12       0
Bank Sta=465.8,495.8
XS Rating Curve= 0 ,0
Exp/Cntr=0.3,0.1

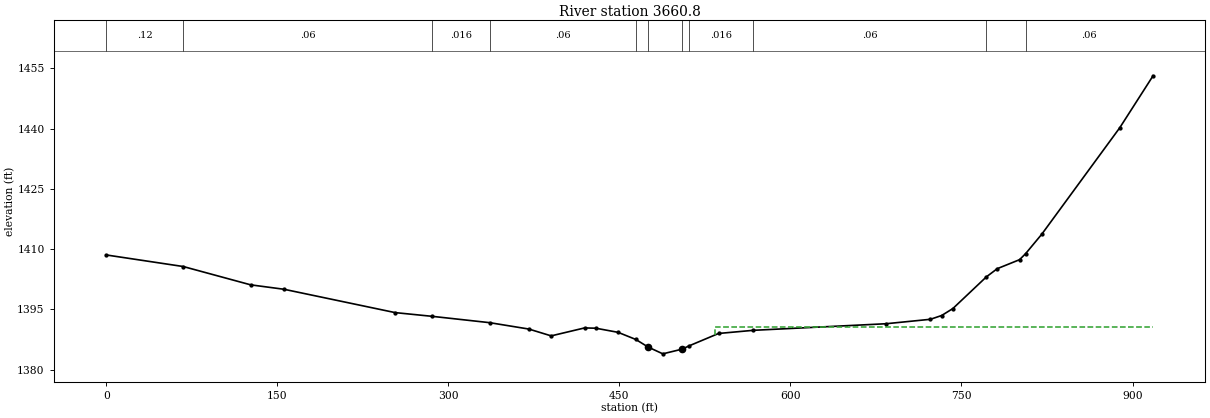
Type RM Length L Ch R = 1 ,3660.8  ,187.6,199,210
XS GIS Cut Line= 4
     1855654.469      250176.637     1855368.011      250299.901
     1855124.955      250555.109     1855052.039      250798.165
#Sta/Elev= 30
       0 1408.54   67.521405.662   126.7  1401.1   155.9    1400   253.4 1394.19
  285.551393.273  336.231391.688   370.6  1390.1   390.2  1388.4   419.5 1390.38
   429.3 1390.31   448.9 1389.28  464.391387.511   475.31385.606   488.1 1383.93
   505.31385.117  510.871385.884     537    1389  567.28 1389.78   683.8 1391.42
   722.8 1392.53   732.6 1393.47   742.4 1395.19  771.871403.098   781.4 1405.13
   800.9 1407.36  806.181408.847   820.4  1413.7   888.8  1440.2     918 1453.13
#Mann= 11 ,-1 , 0
       0     .12       0   67.52     .06       0  285.55    .016       0
  336.23     .06       0  464.39     .12       0   475.3    .045       0
   505.3     .12       0  510.87    .016       0  567.28     .06       0
  771.87    .016       0  806.18     .06       0
#XS Ineff= 2 , 0
                          533.54         1390.54
Permanent Ineff=
       F       F
Bank Sta=475.3,505.3
XS Rating Curve= 0 ,0
Exp/Cntr=0.3,0.1