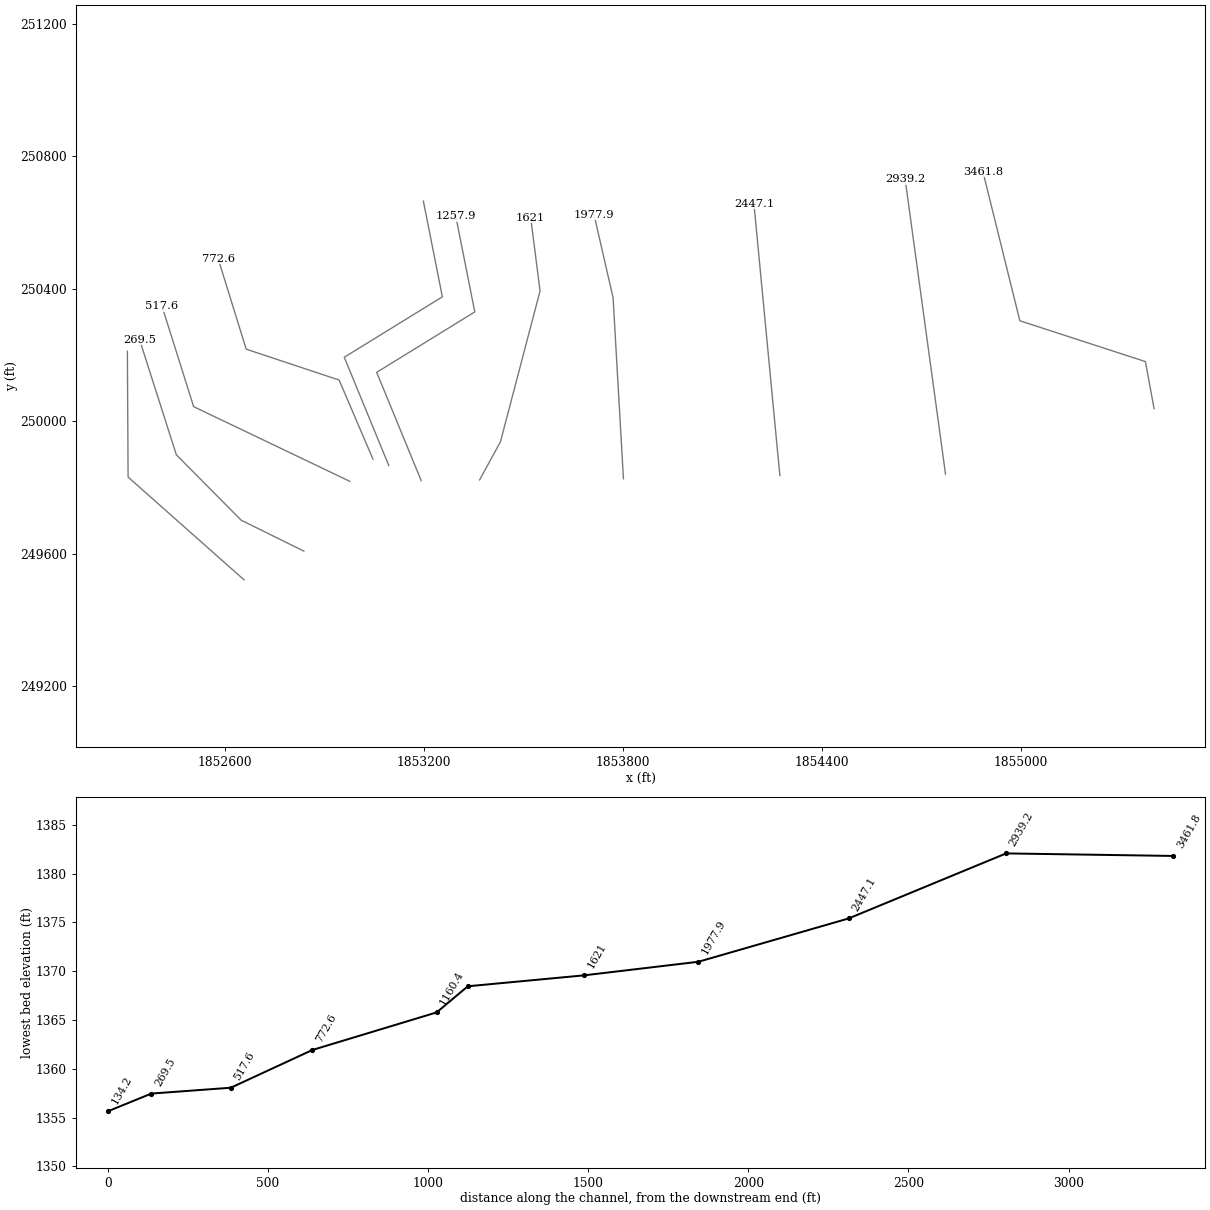
HEC-RAS study BUSHYFK.prj: BUSHYFK

--- BUSHYFK.g01 (geometry) --- (continued)

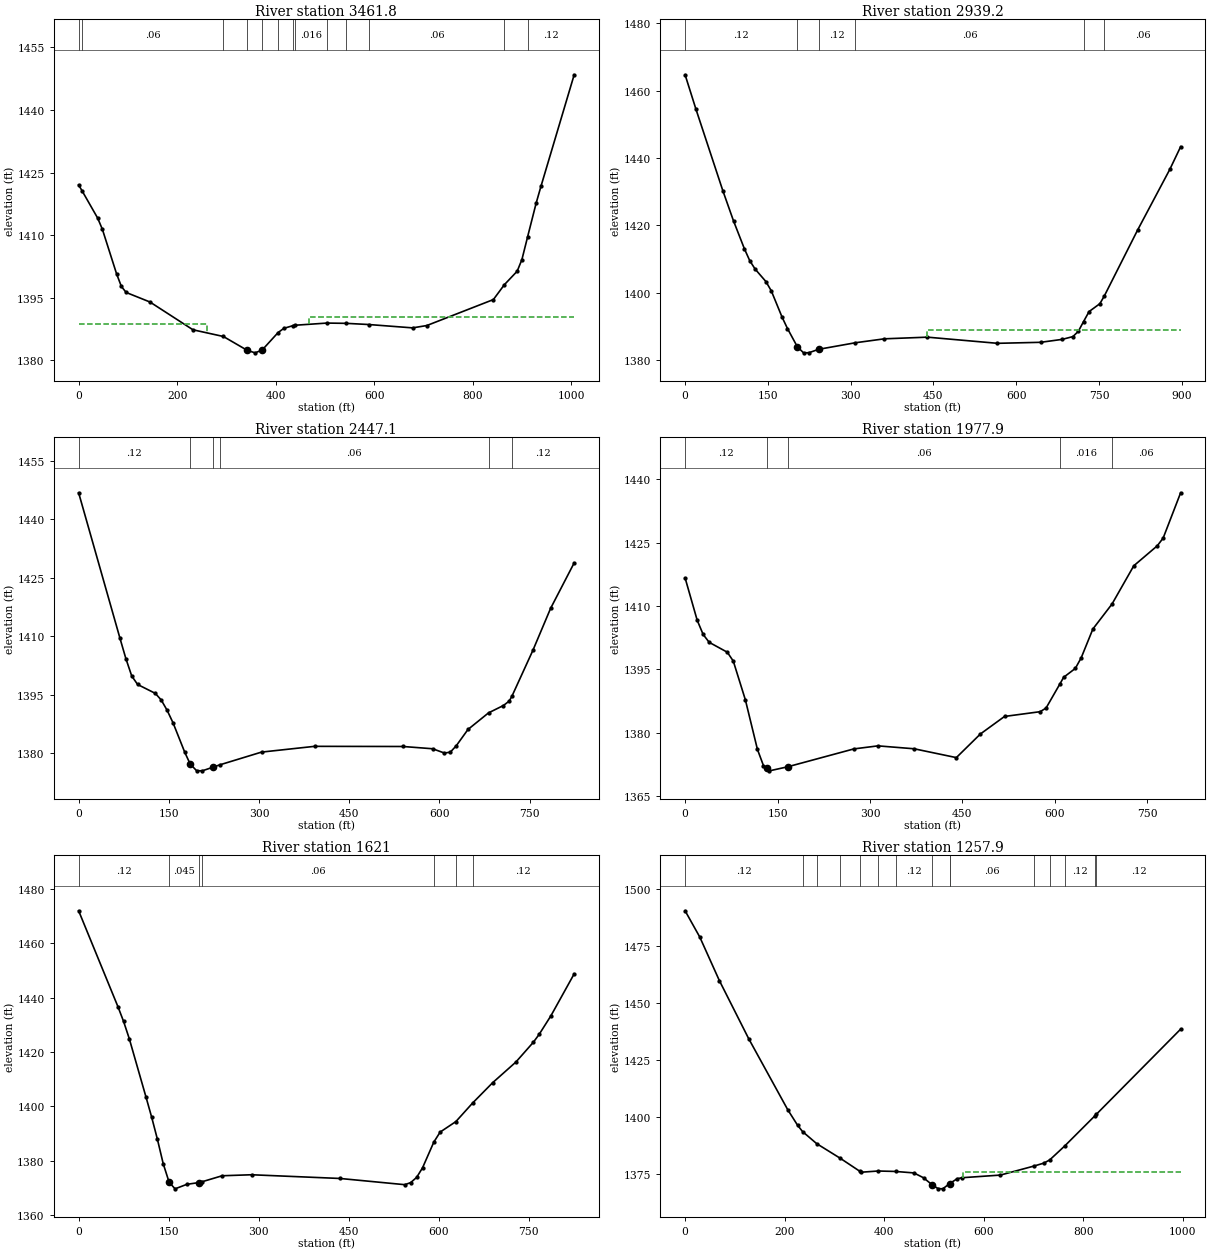
Type RM Length L Ch R = 1 ,3461.8  ,547.8,522.6,496.5
XS GIS Cut Line= 4
     1855400.997      250037.748     1855374.955      250180.109
     1854996.483      250303.373     1854885.372      250753.026
#Sta/Elev= 30
       0 1422.03    7.091420.605    38.6  1414.1    48.2 1411.41    77.2 1400.68
    86.8 1397.72    96.5 1396.28   144.7    1394   232.1 1387.34  293.771385.739
  342.471382.402   358.3 1381.82  372.621382.506  404.951386.684   416.6 1387.69
  435.851388.357  439.331388.429  504.05 1388.95  543.611388.882  588.781388.603
   677.9  1387.8   706.8 1388.36   841.9 1394.58  864.251398.145   890.2 1401.37
   899.8 1404.15  911.451409.642   928.7 1417.67   938.4 1421.67  1005.9 1448.42
#Mann= 13 ,-1 , 0
       0     .12       0    7.09     .06       0  293.77    .016       0
  342.47    .045       0  372.62     .12       0  404.95     .06       0
  435.85     .12       0  439.33    .016       0  504.05     .08       0
  543.61    .016       0  588.78     .06       0  864.25    .016       0
  911.45     .12       0
#XS Ineff= 2 , 0
          260.06 1388.63  468.11         1390.41
Permanent Ineff=
       F       F
Bank Sta=342.47,372.62
XS Rating Curve= 0 ,0
Exp/Cntr=0.3,0.1

Type RM Length L Ch R = 1 ,2939.2  ,492.9,492.1,491
XS GIS Cut Line= 2
     1854772.525      249840.265     1854650.997      250730.022
#Sta/Elev= 30
       0 1464.75    19.5  1454.6    68.3 1430.33    87.8 1421.28   107.4 1413.04
   117.1  1409.5   126.9 1406.98   146.4 1403.28   156.2 1400.51   175.7 1392.71
   185.5 1389.31  203.36  1383.9   214.7 1382.08   224.5 1382.12   241.81383.123
   308.61385.079   361.2 1386.25   439.2 1386.74   566.1 1384.91   644.2 1385.21
   683.3 1386.08   702.8 1386.91   712.6 1388.48  722.081391.383   732.1 1394.35
   751.6 1396.69  759.511398.926   819.9 1418.55   878.5 1436.66     898 1443.37
#Mann= 6 ,-1 , 0
       0     .12       0  203.36    .045       0   241.8     .12       0
   308.6     .06       0  722.08    .016       0  759.51     .06       0
#XS Ineff= 2 , 0
                           438.6         1388.95
Permanent Ineff=
       F       F
Bank Sta=203.36,241.8
XS Rating Curve= 0 ,0
Exp/Cntr=0.3,0.1

Type RM Length L Ch R = 1 ,2447.1  ,470,469.3,468.3
XS GIS Cut Line= 2
     1854273.393      249835.925     1854195.268      250656.238
#Sta/Elev= 30
       0  1446.8    68.7 1409.47    78.5 1404.25    88.3 1399.76    98.1 1397.58
   127.5  1395.3   137.3 1393.61   147.2 1390.94     157 1387.73   176.6 1380.13
  185.511377.157   196.2 1375.44   205.5 1375.41   223.31376.339  235.251376.972
   304.1 1380.22   392.4  1381.7   539.5 1381.66   588.6 1381.08   608.2 1379.98
     618  1380.2   627.8 1381.82   647.4 1386.03  681.571390.289   706.3 1392.18
   716.1 1393.33  720.961394.724   755.4 1406.36   784.8 1417.12     824  1428.8
#Mann= 6 ,-1 , 0
       0     .12       0  185.51    .045       0   223.3     .12       0
  235.25     .06       0  681.57    .016       0  720.96     .12       0
Bank Sta=185.51,223.3
XS Rating Curve= 0 ,0
Exp/Cntr=0.3,0.1

Type RM Length L Ch R = 1 ,1977.9  ,363.9,356.9,350.2
XS GIS Cut Line= 3
     1853802.039      249826.376     1853770.789      250373.251
     1853713.497      250623.251
#Sta/Elev= 30
       0 1416.62    19.6 1406.62    29.3 1403.24    39.1 1401.38    68.5 1399.04
    78.2 1396.94    97.8 1387.78   117.4 1376.04   127.2  1372.2  132.361371.546
   136.9 1370.97   166.51371.928   273.9 1376.16     313 1376.88   371.7 1376.19
   440.2  1374.1   479.3  1379.7   518.4 1383.84   576.3 1384.97   585.8 1385.83
  608.671391.636   614.3  1393.1   633.3 1395.21   642.8 1397.71   661.8 1404.54
  692.851410.447   728.2  1419.5   766.2 1424.21   775.8 1426.04   804.2 1436.77
#Mann= 5 ,-1 , 0
       0     .12       0  132.36    .045       0   166.5     .06       0
  608.67    .016       0  692.85     .06       0
Bank Sta=132.36,166.5
XS Rating Curve= 0 ,0
Exp/Cntr=0.3,0.1

Type RM Length L Ch R = 1 ,1621    ,380.8,363,345.1
XS GIS Cut Line= 4
     1853368.467      249822.691     1853431.401      249937.709
     1853550.759      250393.438     1853522.547      250614.792
#Sta/Elev= 30
       0 1472.02    65.6 1436.62    74.9 1431.24    84.3 1424.94   112.4 1403.25
   121.7 1395.93   131.1 1387.94   140.9 1378.83   150.7 1372.03   160.6 1369.58
   180.2 1371.24   199.8 1371.87  204.681372.129   239.1  1374.4   288.1 1374.77
   435.4  1373.4   543.3 1371.11   553.1 1371.88     563  1373.8   572.8 1377.31
  591.681386.826   602.2  1390.5  628.331394.353  656.351401.221   689.5 1408.66
   728.3 1416.29   757.4 1423.58   767.1  1426.5   786.6 1433.31   825.4 1448.78
#Mann= 7 ,-1 , 0
       0     .12       0   150.7    .045       0   199.8     .12       0
  204.68     .06       0  591.68    .016       0  628.33     .06       0
  656.35     .12       0
Bank Sta=150.7,199.8
XS Rating Curve= 0 ,0
Exp/Cntr=0.3,0.1

Type RM Length L Ch R = 1 ,1257.9  ,98.5,97.5,97.5
XS GIS Cut Line= 4
     1853192.686      249820.521     1853058.495      250147.637
     1853354.067      250330.121     1853296.853      250619.132
#Sta/Elev= 30
       0 1490.59    29.5 1479.05    68.8 1459.95   127.7 1434.44   206.2 1403.22
   225.9 1396.42  236.01 1393.61  264.411388.303  311.981381.847  350.731376.217
   353.6 1375.76  387.941376.293  423.011376.094   459.7 1375.45     479 1373.32
   496.51370.199     508 1368.59   517.6 1368.46   531.51370.756   531.61370.775
   546.6  1372.9   556.2 1373.34   633.4  1374.5  701.111378.477   720.6 1379.75
  732.491381.145   762.71387.284  823.551400.581  826.371401.228   995.6  1438.6
#Mann= 15 ,-1 , 0
       0     .12       0  236.01     .08       0  264.41     .12       0
  311.98     .06       0  350.73    .016       0  387.94     .08       0
  423.01     .12       0   496.5    .045       0   531.5     .12       0
   531.6     .06       0  701.11    .016       0  732.49     .06       0
   762.7     .12       0  823.55     .06       0  826.37     .12       0
#XS Ineff= 2 , 0
                          558.31         1375.84
Permanent Ineff=
       F       F
Bank Sta=496.5,531.5
XS Rating Curve= 0 ,0
Exp/Cntr=0.3,0.1

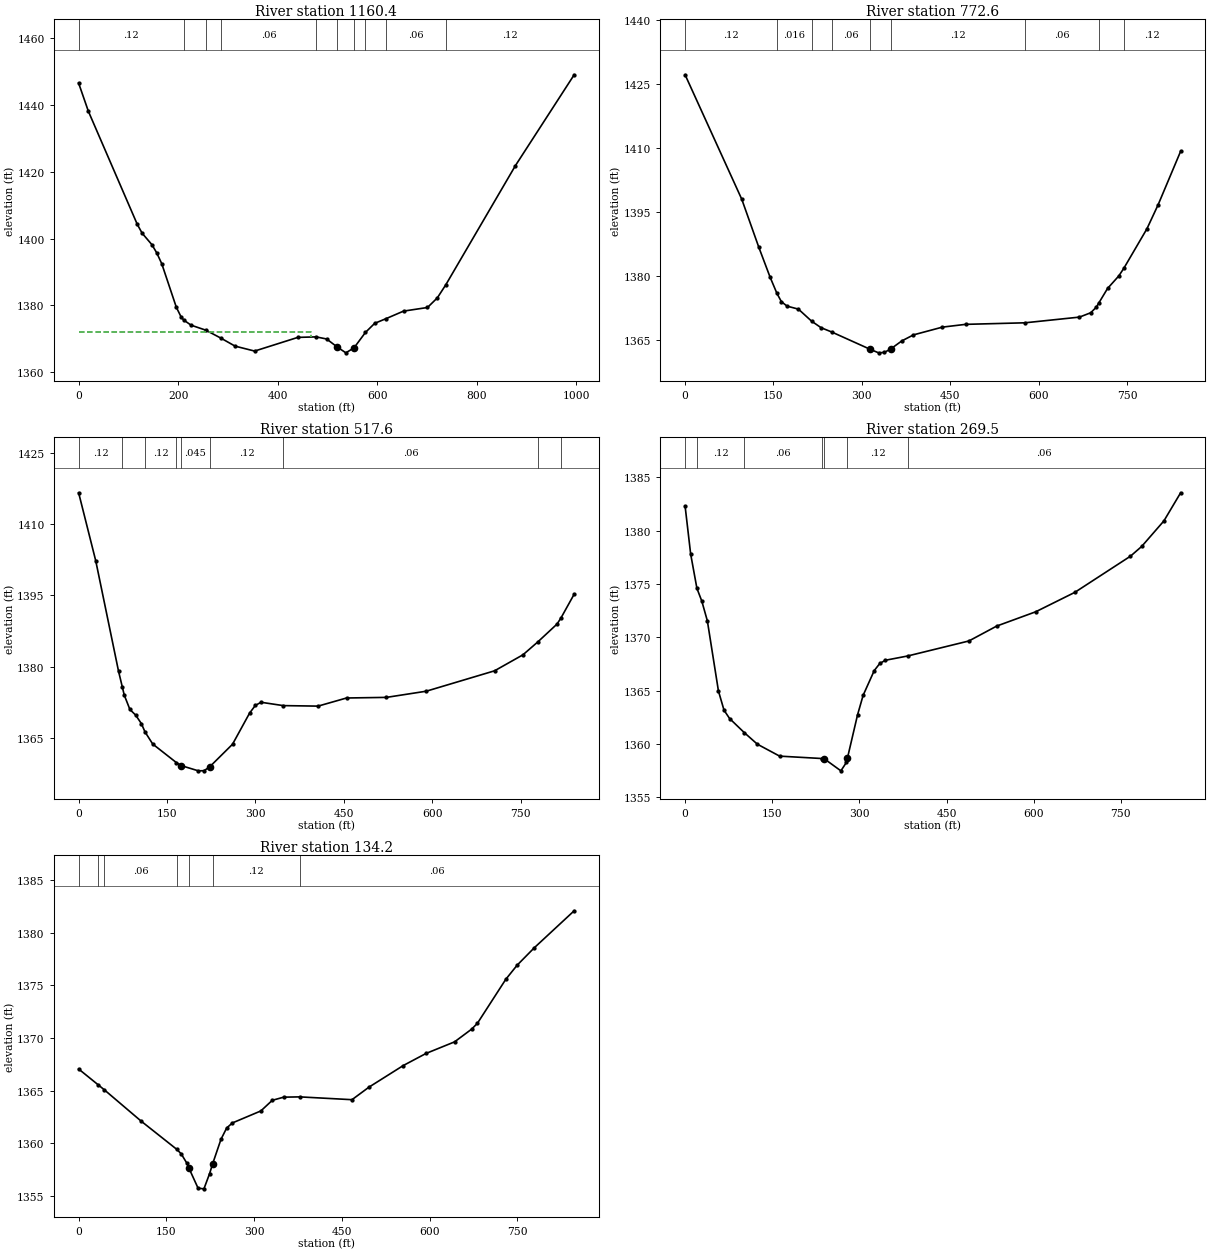
Type RM Length L Ch R = 1 ,1160.4  ,335,387.9,439.7
XS GIS Cut Line= 4
      1853095.03      249866.094     1852960.839       250193.21
      1853256.41      250375.693     1853199.197      250664.705
#Sta/Elev= 30
       0  1446.6    19.6 1438.16   117.9 1404.26   127.7 1401.61   147.3 1398.18
   157.1 1395.69     167 1392.49   196.4 1379.39   206.2 1376.45  211.531375.562
   225.9 1374.07  255.471372.577  286.071370.168   314.3 1367.79   353.6 1366.31
   440.4 1370.41  477.031370.563   498.3 1369.93   518.31367.664   536.9 1365.78
   553.31367.278  576.32 1371.91   594.8 1374.62  617.651376.028   652.7 1378.28
   700.9 1379.37   720.6 1382.24  737.731386.183   877.7 1421.92   995.6 1449.11
#Mann= 10 ,-1 , 0
       0     .12       0  211.53    .016       0  255.47     .08       0
  286.07     .06       0  477.03     .12       0   518.3    .045       0
   553.3     .12       0  576.32    .016       0  617.65     .06       0
  737.73     .12       0
#XS Ineff= 2 , 0
          466.46 1372.16
Permanent Ineff=
       F       F
Bank Sta=518.3,553.3
XS Rating Curve= 0 ,0
Exp/Cntr=0.3,0.1

Type RM Length L Ch R = 1 ,772.6   ,257.8,254.9,252.1
XS GIS Cut Line= 4
     1853047.287      249885.625      1852945.29      250124.341
     1852665.342      250217.657     1852580.707      250491.094
#Sta/Elev= 30
       0 1427.14    96.2 1397.94     125 1386.72   144.2 1379.69  155.66 1375.93
   163.4 1373.93   173.1 1372.88   192.3 1372.18  214.521369.375   230.8 1367.82
   248.71366.824   314.41362.737   328.4 1361.93   338.3 1362.03   349.41362.895
   367.8 1364.73   387.5 1366.14   436.6 1367.96     476 1368.61  576.751368.974
   669.2 1370.31   688.3 1371.33   697.8 1372.64  702.071373.629   716.9 1377.03
     736 1379.97  744.541381.768   783.7 1391.02   802.8 1396.69   840.9  1409.2
#Mann= 9 ,-1 , 0
       0     .12       0  155.66    .016       0  214.52     .12       0
   248.7     .06       0   314.4    .045       0   349.4     .12       0
  576.75     .06       0  702.07    .016       0  744.54     .12       0
Bank Sta=314.4,349.4
XS Rating Curve= 0 ,0
Exp/Cntr=0.3,0.1

Type RM Length L Ch R = 1 ,517.6   ,256,248.1,240.4
XS GIS Cut Line= 3
     1852977.842      249818.351     1852506.922      250044.046
     1852411.436      250347.865
#Sta/Elev= 30
       0 1416.58      29 1402.28    67.7 1379.03   74.291375.613    77.4    1374
      87 1370.97    96.7  1369.8   106.4 1368.01  112.591366.256   125.7  1363.7
  165.661359.813   174.1 1359.16   203.1 1358.06   212.8 1358.09   222.4 1358.91
   261.1 1363.66   290.1 1370.22   299.8 1371.83   309.5 1372.49  347.051371.789
   406.2 1371.68   454.5 1373.39   522.2 1373.52   589.8 1374.82   705.6 1379.11
   753.8 1382.48  778.831385.172   811.7 1388.96  818.661390.316   840.7 1395.24
#Mann= 9 ,-1 , 0
       0     .12       0   74.29    .016       0  112.59     .12       0
  165.66     .06       0   174.1    .045       0   222.4     .12       0
  347.05     .06       0  778.83    .016       0  818.66     .06       0
Bank Sta=174.1,222.4
XS Rating Curve= 0 ,0
Exp/Cntr=0.3,0.1

Type RM Length L Ch R = 1 ,269.5   ,133.7,135.4,136.8
XS GIS Cut Line= 4
     1852838.954      249607.848     1852650.151      249701.164
     1852454.839      249898.646     1852344.162      250245.869
#Sta/Elev= 30
       0 1382.31     9.6  1377.8   20.351374.587    28.7  1373.4    38.3 1371.54
    57.4 1364.95      67 1363.15    76.6 1362.37  101.661361.057   124.4 1359.96
   162.7 1358.84  235.741358.615   239.3  1358.6   268.1 1357.46   277.6 1358.25
  279.45 1358.67   296.8 1362.72   306.4 1364.55   325.5 1366.87   335.1 1367.54
   344.7 1367.84  382.891368.239   488.4 1369.65   536.3 1371.05   603.4 1372.39
   670.6 1374.21   766.5 1377.61   785.7 1378.52     824 1380.92   852.8 1383.56
#Mann= 7 ,-1 , 0
       0    .016       0   20.35     .12       0  101.66     .06       0
  235.74     .12       0   239.3    .045       0  279.45     .12       0
  382.89     .06       0
Bank Sta=239.3,279.45
XS Rating Curve= 0 ,0
Exp/Cntr=0.3,0.1

Type RM Length L Ch R = 1 ,134.2   ,141,134.2,127.3
XS GIS Cut Line= 3
     1852658.832      249521.042      1852309.44      249831.372
      1852307.27      250211.146
#Sta/Elev= 30
       0 1367.05   32.791365.573   43.711365.079   107.1 1362.08  167.48 1359.42
   175.2 1358.99     185 1358.09  188.361357.643   204.2 1355.71   214.2 1355.65
   223.9  1357.1   229.21358.052   243.4 1360.37   253.1 1361.44   262.9 1361.92
   311.5 1363.06     331 1364.07   350.5 1364.37  377.851364.398   467.3 1364.13
   496.5 1365.33     555 1367.38   593.9 1368.53   642.6 1369.63   671.8 1370.84
   681.6 1371.39   730.2 1375.58   749.7 1376.93   778.9 1378.58   847.1  1382.1
#Mann= 7 ,-1 , 0
       0     .06       0   32.79     .12       0   43.71     .06       0
  167.48     .12       0  188.36    .045       0   229.2     .12       0
  377.85     .06       0
Bank Sta=188.36,229.2
XS Rating Curve= 0 ,0
Exp/Cntr=0.3,0.1

Chan Stop Cuts=-1
Use User Specified Reach Order=0
Composite Channel Slope=5